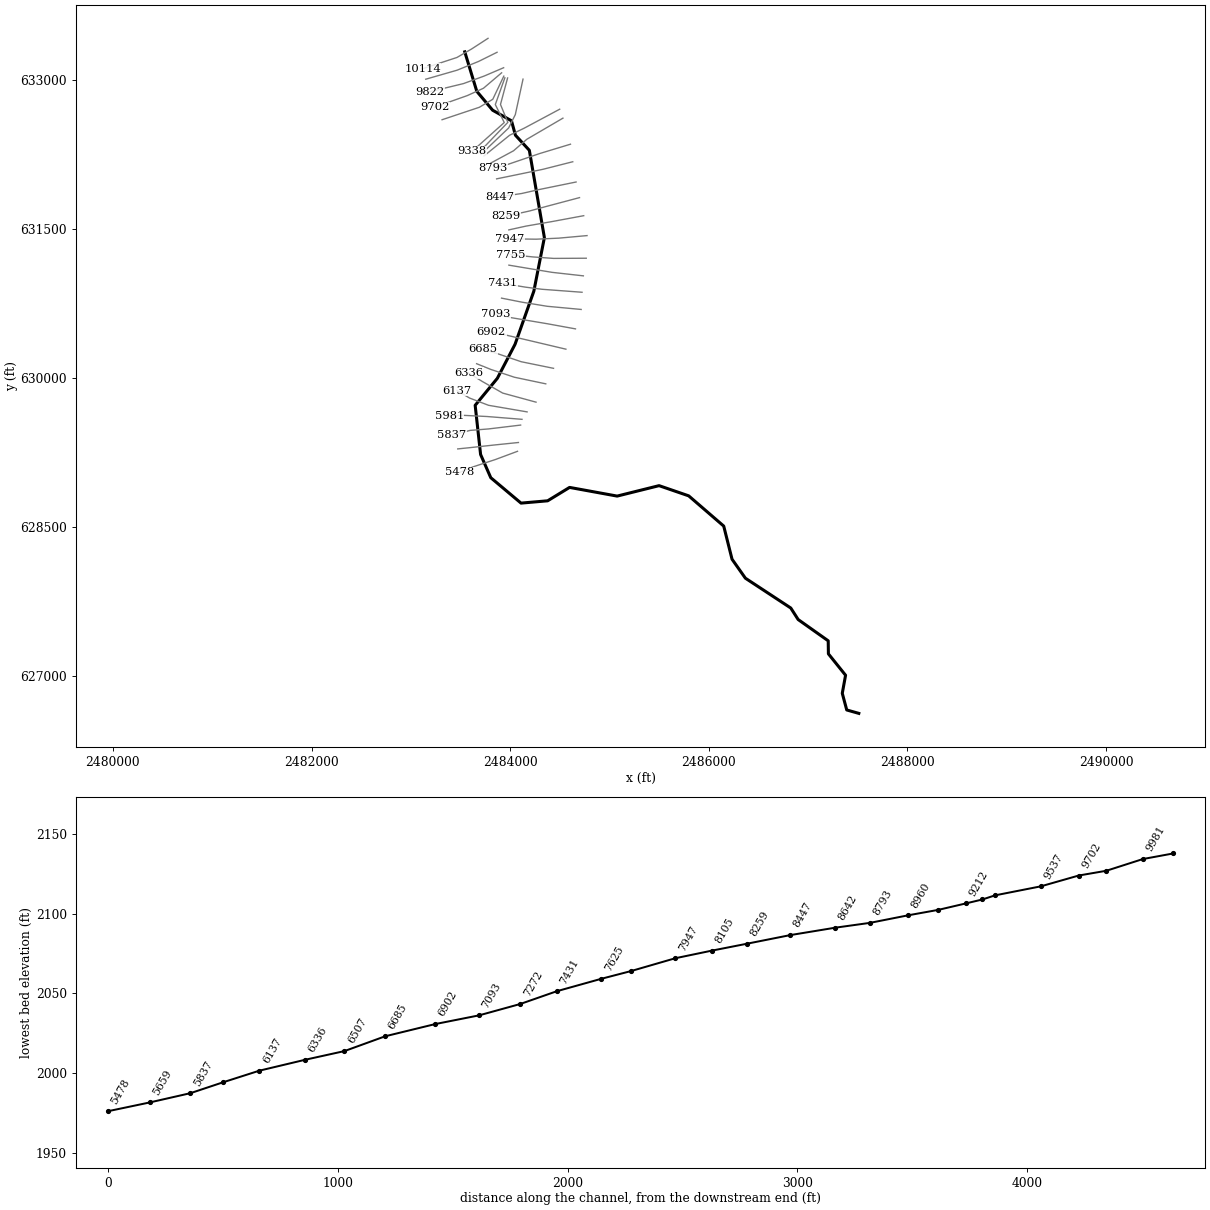
--- SFSBPOTOMC_T1.prj (project) ---

Proj Title=SFSBPOTOMC_T1
Current Plan=p01
Default Exp/Contr=0,0
English Units
Geom File=g01
Flow File=f01
Plan File=p01
BEGIN DESCRIPTION:
Stream Name: South Fork South Branch Potomac River Tributary 1
Flood Zone: Zone A
Pendleton County, WV
WVDHSEM Flood Warning & Analysis Mapping
HEC-RAS Version: 5.0.7
Hydrology Method:
Regression
Model Notes:
Tie in with SFSBPOTOMC at the downstream end.
END DESCRIPTION:
DSS Export Rating Curves= 0
DSS Export Rating Curve Sorted= 0
DSS Export Volume Flow Curves= 0
DXF OffsetX= 0
DXF OffsetY= 0
DXF ScaleX= 0
DXF ScaleY= 0

--- SFSBPOTOMC_T1.p01 (plan) ---

Plan Title=Floodplain
Program Version=5.07
Short Identifier=Floodplain
Geom File=g01
Flow File=f01
Subcritical Flow
K Sum by GR= 0
Std Step Tol= 0.01
Critical Tol= 0.01
Num of Std Step Trials= 20
Max Error Tol= 0.3
Flow Tol Ratio= 0.001
Split Flow NTrial= 30
Split Flow Tol= 0.02
Split Flow Ratio= 0.02
Log Output Level= 0
Friction Slope Method= 1
Unsteady Friction Slope Method= 2
Unsteady Bridges Friction Slope Method= 1
Parabolic Critical Depth
Global Vel Dist= 0 , 0 , 0
Global Log Level= 0
CheckData=True
Encroach Param=-1 ,0,0, 0
Mapping Interval=1HOUR
Computation Time Step Use Courant=        0
Computation Time Step Use Time Series=    0
Computation Time Step Count To Double=0
Computation Time Step Max Doubling=0
Computation Time Step Max Halving=0
Computation Time Step Residence Courant=0
Run HTab= 0
Run UNet= 0
Run Sediment= 0
Run PostProcess= 0
Run WQNet= 0
Run RASMapper= 0
UNET Theta= 0
UNET Theta Warmup= 0
UNET ZTol= 0
UNET ZSATol= 0
UNET MxIter= 0
UNET Max Iter WO Improvement= 0
UNET MaxInSteps= 0
UNET DtIC= 0
UNET DtMin= 0
UNET MaxCRTS= 0
UNET WFStab= 0
UNET SFStab= 0
UNET WFX= 1
UNET SFX= 1
UNET 1D Methodology=Finite Difference
UNET DSS MLevel= 1
UNET Pardiso=0
UNET DZMax Abort= 0
UNET Use Existing IB Tables= 0
UNET Froude Reduction=False
UNET Froude Limit= 0
UNET Froude Power= 0
UNET D1 Cores= 0
UNET D2 Coriolis=0
UNET D2 Cores= 0
UNET D2 Theta= 1
UNET D2 Theta Warmup= 1
UNET D2 Z Tol= 0.01
UNET D2 Volume Tol= 0.01
UNET D2 Max Iterations= 20
UNET D2 Equation= 0
UNET D2 RampUpFraction=0.1
UNET D2 TimeSlices= 1
UNET D2 BCVolumeCheck=0
UNET D1D2 MaxIter= 0
UNET D1D2 ZTol=0.01
UNET D1D2 QTol=0.1
UNET D1D2 MinQTol=1
Write IC File= 0
Write IC File at Fixed DateTime=0
Write IC File at Sim End=0
Echo Input=False
Echo Parameters=False
Echo Output=False
Write Detailed= 0
HDF Write Warmup=0
HDF Write Time Slices=0
HDF Flush=0
HDF Face Node Velocities=0
HDF Compression= 1
HDF Chunk Size= 1
HDF Spatial Parts= 1
HDF Use Max Rows=0
HDF Fixed Rows= 1
Calibration Method= 0
Calibration Iterations= 20
Calibration Max Change=0.05
Calibration Tolerance=0.2
Calibration Maximum=1.5
Calibration Minimum=0.5
Calibration Optimization Method= 1
WQ AD Non Conservative
WQ ULTIMATE=-1
WQ Max Comp Step=1HOUR
WQ Output Interval=15MIN
WQ Output Selected Increments= 0
WQ Output face flow=0
WQ Output face velocity=0
WQ Output face area=0
WQ Output face dispersion=0
WQ Output cell volume=0
WQ Output cell surface area=0
WQ Output cell continuity=0
WQ Output cumulative cell continuity=0
WQ Output face conc=0
WQ Output face dconc_dx=0
WQ Output face courant=0
WQ Output face peclet=0
WQ Output face adv mass=0
WQ Output face disp mass=0
WQ Output cell mass=0
WQ Output cell source sink temp=0
WQ Output nsm pathways=0
WQ Output nsm derived pathways=0
WQ Output MaxMinRange=-1
WQ Daily Max Min Mean=-1
WQ Daily Range=0
WQ Daily Time=0
WQ Create Restart=0
WQ Fixed Restart=0
WQ System Summary=0
WQ Write To DSS=0
WQ Use Fixed Temperature=0
Sorting and Armoring Iterations= 10
XS Update Threshold= 0.02
Bed Roughness Predictor= 0
Hydraulics Update Threshold= 0.02
Energy Slope Method= 1
Volume Change Method= 1
Sediment Retention Method= 0
XS Weighting Method= 0
Number of US Weighted Cross Sections= 1
Number of DS Weighted Cross Sections= 1
Upstream XS Weight=0
Main XS Weight=1
Downstream XS Weight=0
Number of DS XS's Weighted with US Boundary= 1
Upstream Boundary Weight= 1
Weight of XSs Associated with US Boundary= 0
Number of US XS's Weighted with DS Boundary= 1
Downstream Boundary Weight= 0.5
Weight of XSs Associated with DS Boundary= 0.5
Percentile Method= 0
Sediment Output Level= 3
Mass or Volume Output= 0
Output Increment Type= 1
Profile and TS Output Increment= 1
XS Output Flag= 0
XS Output Increment= 10
Write Gradation File= 0
Read Gradation Hotstart= 0
Write HDF5 File= 1
Write Binary Output= 1
Write DSS Sediment File= 0
SV Curve= 0
Specific Gage Flag= 0

--- SFSBPOTOMC_T1.f01 (steady flow) ---

Flow Title=Flows
Program Version=5.07
Number of Profiles= 6
Profile Names=P100yr,P10yr,P25yr,P50yr,P500yr,P101yr
River Rch & RM=SFSBPOTOMC_T1,Main            ,10114
     604     282     399     498     885     735
River Rch & RM=SFSBPOTOMC_T1,Main            ,9091
     678     316     447     559     995     825
River Rch & RM=SFSBPOTOMC_T1,Main            ,5478
     759     354     501     626    1115     924
Boundary for River Rch & Prof#=SFSBPOTOMC_T1,Main            , 1
Up Type= 0
Dn Type= 3
Dn Slope=0.03311
Boundary for River Rch & Prof#=SFSBPOTOMC_T1,Main            , 2
Up Type= 0
Dn Type= 3
Dn Slope=0.03311
Boundary for River Rch & Prof#=SFSBPOTOMC_T1,Main            , 3
Up Type= 0
Dn Type= 3
Dn Slope=0.03311
Boundary for River Rch & Prof#=SFSBPOTOMC_T1,Main            , 4
Up Type= 0
Dn Type= 3
Dn Slope=0.03311
Boundary for River Rch & Prof#=SFSBPOTOMC_T1,Main            , 5
Up Type= 0
Dn Type= 3
Dn Slope=0.03311
Boundary for River Rch & Prof#=SFSBPOTOMC_T1,Main            , 6
Up Type= 0
Dn Type= 3
Dn Slope=0.03311
DSS Import GetInterval= 0
DSS Import GetPeak= 0
DSS Import FillOption= 0

--- SFSBPOTOMC_T1.g01 (geometry) ---

Geom Title=Geometry
Program Version=5.07

River Reach=SFSBPOTOMC_T1   ,Main
Reach XY= 30
     2483543.004      633281.404     2483664.092      632883.666
     2483823.585      632693.563     2484013.113      632587.239
     2484053.066      632441.958     2484193.038      632290.016
     2484344.541      631411.354     2484238.313      630871.267
     2484049.111      630336.914     2483871.216      629994.891
     2483647.659       629722.61     2483702.272      629227.771
     2483804.785      628993.815     2484109.364      628737.962
     2484377.363       628761.23     2484598.121      628896.077
     2485077.054       628808.67     2485499.132      628913.784
     2485797.459      628811.095     2486150.014      628506.817
     2486233.875      628172.913      2486368.41      627981.894
     2486825.146      627681.835     2486899.504       627565.79
     2487202.135      627351.585     2487203.999      627220.373
      2487376.86      627005.007     2487343.739      626823.238
     2487388.623      626655.369     2487510.298      626621.067

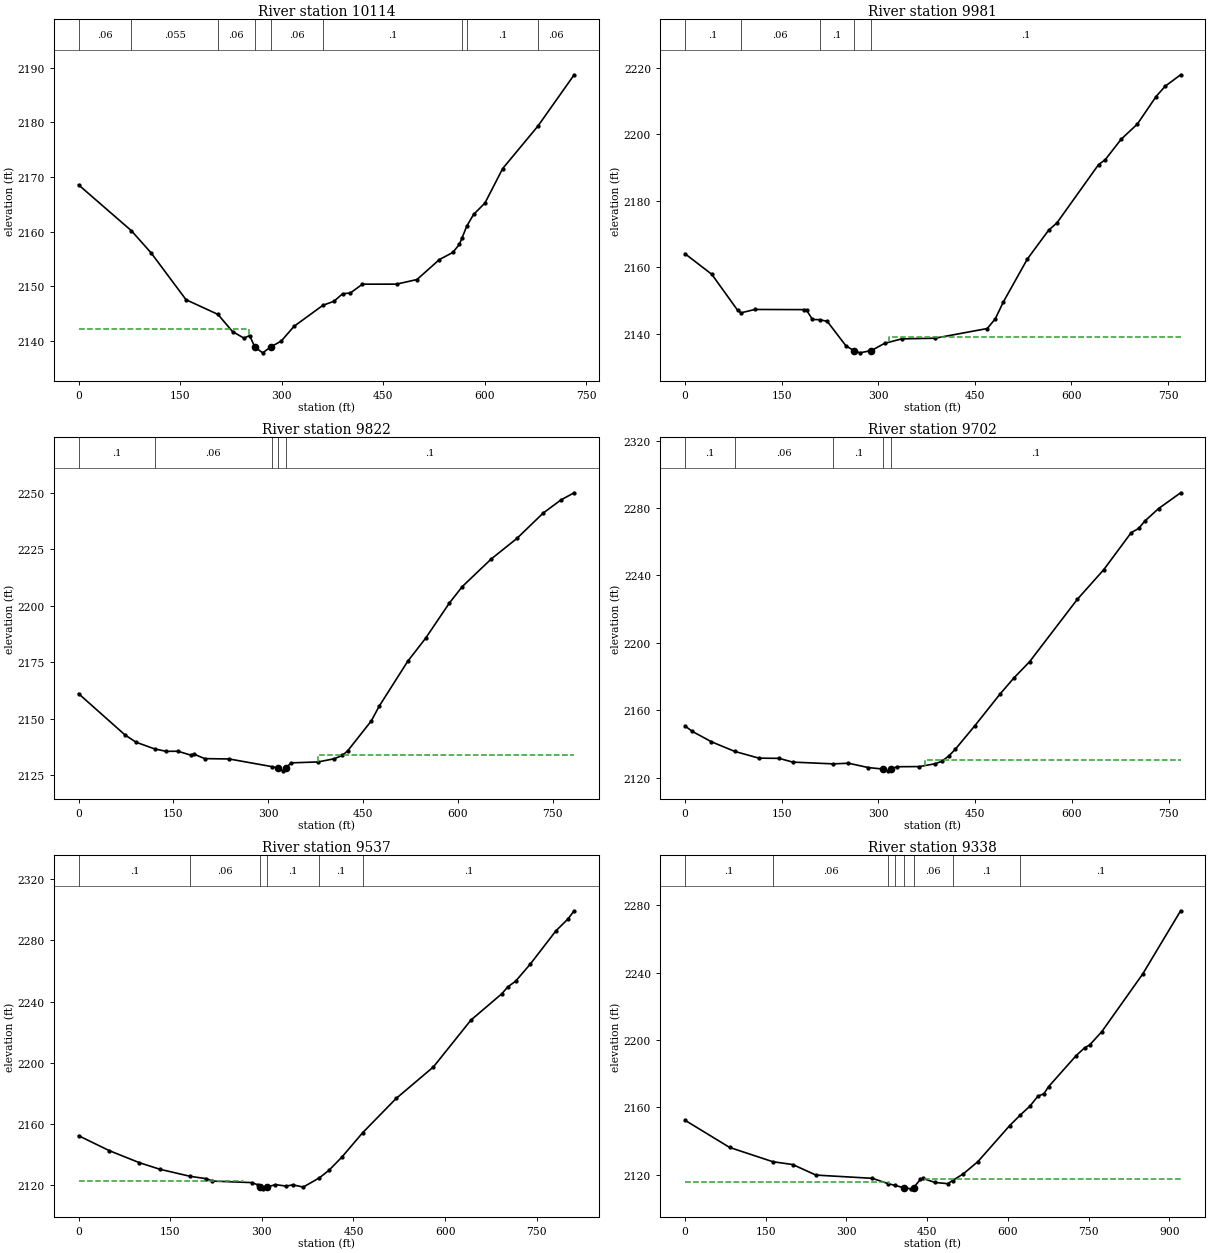
Type RM Length L Ch R = 1 ,10114   ,136.9,133.2,132.1
XS GIS Cut Line= 4
2483777.13912588633417.3489090592483613.77133686633311.380613473
 2483464.5326539633224.8398387442483117.48648586633110.923920989
#Sta/Elev= 30
       0 2168.57   78.172160.168   107.4  2156.1   158.9 2147.55  206.022144.866
   227.6 2141.72   244.5 2140.52   252.9 2140.99  260.562138.884   272.2 2137.83
  283.772138.884   299.7 2139.99   318.4 2142.67  361.222146.531   377.5 2147.26
   390.2 2148.63   401.9 2148.79   419.6 2150.39   470.2  2150.4   500.2 2151.24
   533.3 2154.89   553.1 2156.19   562.8 2157.67  567.052158.917  573.752161.006
   583.8 2163.14   600.7 2165.24   626.9 2171.55  678.892179.306732.5056  2188.7
#Mann= 9 ,-1 , 0
       0     .06       0   78.17    .055       0  206.02     .06       0
  260.56    .045       0  283.77     .06       0  361.22      .1       0
  567.05     .06       0  573.75      .1       0  678.89     .06       0
#XS Ineff= 2 , 0
          251.89 2142.21
Permanent Ineff=
       F       F
Bank Sta=260.56,283.77
XS Rating Curve= 0 ,0
Exp/Cntr(USF)=0,0
Exp/Cntr=0.3,0.1

Type RM Length L Ch R = 1 ,9981    ,163.6,158.6,158.2
XS GIS Cut Line= 4
2483868.09524626633276.9409174072483682.65072899633185.101727899
2483466.29879216633096.7948149112483150.16004366633005.838694532
#Sta/Elev= 30
       0 2164.07    41.7 2157.87    81.9 2147.03   87.112146.315   108.6 2147.32
   184.5 2147.27     189 2147.04   197.9 2144.32  209.082144.244   220.8 2143.77
     250 2136.38  261.98 2134.99   271.6 2134.29  289.54 2134.99   309.8 2137.13
   336.4 2138.48   388.3 2138.69   469.3 2141.59   481.8  2144.5   494.3 2149.57
   531.7  2162.5   564.6 2171.12   577.6 2173.34   642.2 2190.85   652.4 2192.28
   677.4 2198.49   702.4 2203.01   731.5 2211.29   745.6 2214.39   769.6 2217.82
#Mann= 5 ,-1 , 0
       0      .1       0   87.11     .06       0  209.08      .1       0
  261.98    .045       0  289.54      .1       0
#XS Ineff= 2 , 0
                          316.11         2138.97
Permanent Ineff=
       F       F
Bank Sta=261.98,289.54
XS Rating Curve= 0 ,0
Exp/Cntr(USF)=0,0
Exp/Cntr=0.3,0.1

Type RM Length L Ch R = 1 ,9822    ,119.5,120,120.9
XS GIS Cut Line= 4
  2483934.325431633121.5207505472483738.28408417633037.629183208
2483529.87976952632961.6852380382483190.78122364632879.559808958
#Sta/Elev= 30
       0 2161.11    73.5 2142.83    90.9 2139.62   120.3 2136.66   138.7 2135.57
   157.1 2135.62   177.9 2133.88   182.3 2134.37   199.7 2132.35   238.3  2132.2
   305.32128.839  315.622128.218   323.4 2126.95  327.822128.216   336.2 2130.48
   378.8 2130.88   404.3 2132.29   417.1 2133.75   425.6 2135.75   463.2 2149.08
   475.3 2155.44   520.6 2175.37   548.9 2185.58   586.4  2201.1     607 2208.45
   652.7 2220.64   693.4 2229.74   734.8 2240.93   763.4 2246.83   783.9 2249.92
#Mann= 5 ,-1 , 0
       0      .1       0   120.3     .06       0   305.3      .1       0
  315.62    .045       0  327.82      .1       0
#XS Ineff= 2 , 0
                          378.07         2134.07
Permanent Ineff=
       F       F
Bank Sta=315.62,327.82
XS Rating Curve= 0 ,0
Exp/Cntr(USF)=0,0
Exp/Cntr=0.3,0.1

Type RM Length L Ch R = 1 ,9702    ,163,165.2,165.6
XS GIS Cut Line= 4
2483914.01484102633070.3027410142483731.21953113632914.882574154
 2483567.8517421632840.7047672432483238.46695665632724.139642098
#Sta/Elev= 30
       0 2150.63    11.4 2147.39      41 2141.24   77.042135.528   114.6 2131.51
   146.1 2131.38   167.1 2129.16  230.222128.102   253.6 2128.49   284.4 2125.91
  307.712125.015   315.1 2123.97  320.332125.015   328.3 2126.41   363.5  2126.5
   388.3 2128.19   398.6 2129.69   409.5 2132.91   419.4 2136.82   449.9 2150.89
   488.4 2169.44   509.6 2178.88   534.5 2188.76   608.6 2225.84   649.7 2243.49
   692.1  2265.4   703.7 2267.89   713.1 2272.21   734.5 2279.68   768.8 2289.08
#Mann= 5 ,-1 , 0
       0      .1       0   77.04     .06       0  230.22      .1       0
  307.71    .045       0  320.33      .1       0
#XS Ineff= 2 , 0
                          371.74          2130.4
Permanent Ineff=
       F       F
Bank Sta=307.71,320.33
XS Rating Curve= 0 ,0
Exp/Cntr(USF)=0,0
Exp/Cntr=0.3,0.1

Type RM Length L Ch R = 1 ,9537    ,179.9,199.3,221.1
XS GIS Cut Line= 4
2483936.09156926633036.746114078 2483824.8248589632803.615863788
2483689.71528203632723.2565729682483314.41090182632597.860756524
#Sta/Elev= 30
       0 2152.05    50.4 2142.21    99.6 2134.33   133.1 2130.02  183.022125.357
   209.4 2123.83   219.2 2122.27   283.7 2121.27   293.3 2119.85  296.64 2118.26
   301.2 2117.18  307.712118.258   322.3 2119.94   339.9 2118.98   350.8  2119.8
   367.8 2118.34  393.862124.285   409.7 2129.25   430.8 2137.89  465.222154.047
   519.9 2176.45   580.8  2197.1   642.2  2227.8   692.8 2245.07   702.7 2249.63
   715.3 2253.28   739.2 2264.43   781.3 2286.31   800.7 2293.97   811.2 2299.48
#Mann= 6 ,-1 , 0
       0      .1       0  183.02     .06       0  296.64    .045       0
  307.71      .1       0  393.86      .1       0  465.22      .1       0
#XS Ineff= 2 , 0
           269.6 2122.33
Permanent Ineff=
       F       F
Bank Sta=296.64,307.71
XS Rating Curve= 0 ,0
Exp/Cntr(USF)=0,0
Exp/Cntr=0.5,0.3

Type RM Length L Ch R = 1 ,9338    ,62.6,55.2,50
XS GIS Cut Line= 4
2483946.68839882 633019.967800612483850.43386367632750.631715995
2483940.50691491632569.6025443682483618.18668251632280.838938895
#Sta/Elev= 30
       0 2152.26      83  2136.1  163.272127.622   200.2 2125.95   243.3 2119.69
   348.3 2117.76  377.292114.631   390.6 2113.51  406.132112.242   419.8 2111.52
  424.812112.241   437.6 2117.21   442.1 2117.72   464.4 2115.33   488.2 2114.59
  497.242116.467   516.9 2120.35   544.3 2127.69   603.4  2149.1  623.312155.436
     641 2160.64   655.7 2166.52     667 2168.03   675.5 2172.15   726.9 2190.67
     743  2195.4     752 2196.94   774.7 2204.95   850.4 2239.05     921 2276.66
#Mann= 8 ,-1 , 0
       0      .1       0  163.27     .06       0  377.29      .1       0
   390.6     .06       0  406.13    .045       0  424.81     .06       0
  497.24      .1       0  623.31      .1       0
#XS Ineff= 2 , 0
       0  379.18  2115.4  443.75       0 2117.64
Permanent Ineff=
       F       F
Bank Sta=406.13,424.81
XS Rating Curve= 0 ,0
Exp/Cntr(USF)=0,0
Exp/Cntr=0.5,0.3

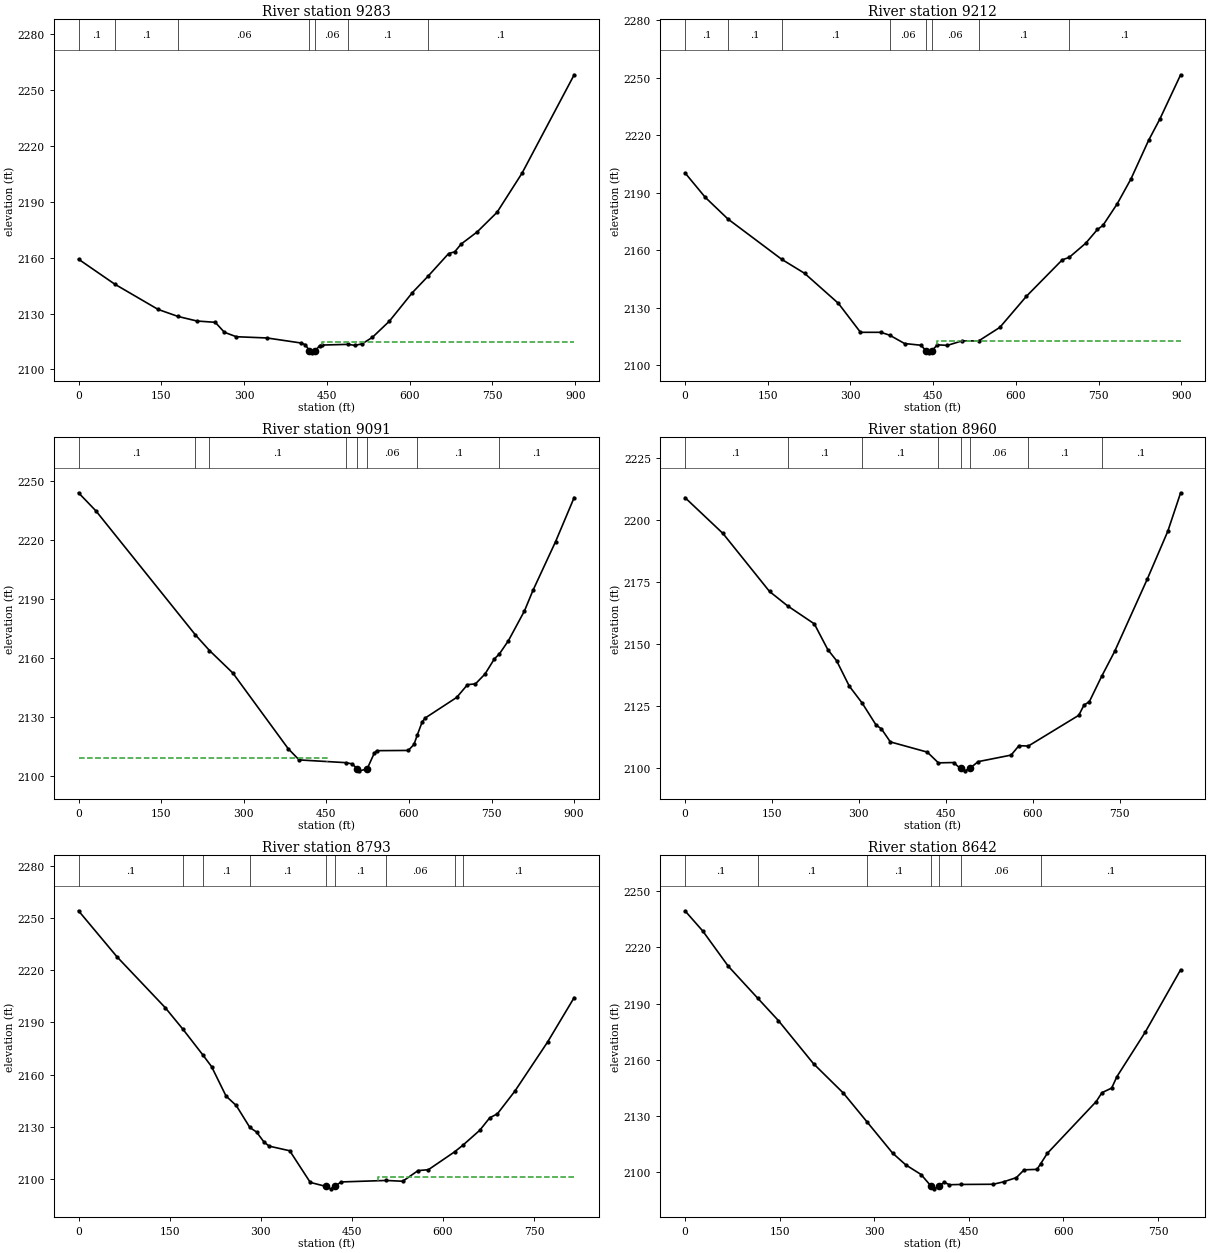
Type RM Length L Ch R = 1 ,9283    ,77.8,70.1,58.9
XS GIS Cut Line= 4
2483974.06354185633018.2016623512483902.53494233632751.514785125
2483976.71274924632571.3686826282483680.88459073632263.177556297
#Sta/Elev= 30
       0 2159.14   65.662145.753   144.2 2132.21   180.42128.432   214.6 2125.99
   247.8 2125.29   264.3 2119.95   285.9 2117.57   341.7  2116.9   402.4 2114.24
   410.9 2113.33   418.4 2110.06   423.7 2108.93  429.252110.059   436.8 2112.82
   441.2  2113.1  488.362113.476     501 2112.92   514.2 2113.81   532.6 2117.27
   563.2 2125.88   604.7 2141.13  633.532150.073   670.7 2162.18   681.7 2163.09
   693.3 2167.25   722.2 2173.72   758.4 2184.28   803.7 2205.28   898.1    2258
#Mann= 7 ,-1 , 0
       0      .1       0   65.66      .1       0   180.4     .06       0
   418.4    .045       0  429.25     .06       0  488.36      .1       0
  633.53      .1       0
#XS Ineff= 2 , 0
                          442.01         2114.91
Permanent Ineff=
       F       F
Bank Sta=418.4,429.25
XS Rating Curve= 0 ,0
Exp/Cntr(USF)=0,0
Exp/Cntr=0.5,0.3

Type RM Length L Ch R = 1 ,9212    ,125.7,121,115.6
XS GIS Cut Line= 4
2484129.48370871633006.7217636622484051.77362528632649.078766058
2483984.66037141632514.8522583152483707.37666463632250.814588479
#Sta/Elev= 30
       0 2200.46    36.7 2187.69   77.922176.356  175.632155.287   216.8 2148.04
   278.2 2132.35   318.3 2117.23   355.2 2117.23  371.292115.725   398.2 2111.38
     428 2110.48  437.392107.478   442.9 2106.52  447.262107.478   457.7 2110.71
   475.8 2110.41   502.7 2112.79  532.512112.718   571.1 2119.82   619.2 2136.03
   684.3 2155.07   696.82156.323   726.8 2163.72     748 2170.89   757.9 2172.98
   783.8 2184.24   808.8 2197.26   840.8  2217.4   861.2  2228.5   898.9 2251.62
#Mann= 8 ,-1 , 0
       0      .1       0   77.92      .1       0  175.63      .1       0
  371.29     .06       0  437.39    .045       0  447.26     .06       0
  532.51      .1       0   696.8      .1       0
#XS Ineff= 2 , 0
                           457.6         2112.46
Permanent Ineff=
       F       F
Bank Sta=437.39,447.26
XS Rating Curve= 0 ,0
Exp/Cntr(USF)=0,0
Exp/Cntr=0.3,0.1

Type RM Length L Ch R = 1 ,9091    ,129.6,131.8,135.5
XS GIS Cut Line= 4
  2484498.606605632703.8290521112484143.61281479632513.969189185
2483994.37413184632441.5575205352483736.51794591632233.153205881
#Sta/Elev= 30
       0  2244.2    31.6 2234.97  212.392171.709  237.842163.778   280.2 2152.32
   380.9 2113.68   400.6 2108.01  485.292106.614   496.9 2105.99  506.542103.384
   510.2 2102.44  523.982103.382   536.9 2111.37   541.4 2112.72   598.8 2112.84
   609.1 2115.87  615.322120.837   624.1 2127.44   629.8 2129.43   686.7 2139.87
   706.3 2146.37   720.8 2146.79   738.1 2151.79     755 2159.47  764.192162.035
   780.6 2168.79   809.7 2183.94   825.1 2194.39   866.3 2219.33     900 2241.78
#Mann= 8 ,-1 , 0
       0      .1       0  212.39      .1       0  237.84      .1       0
  485.29     .06       0  506.54    .045       0  523.98     .06       0
  615.32      .1       0  764.19      .1       0
#XS Ineff= 2 , 0
          451.67 2109.05
Permanent Ineff=
       F       F
Bank Sta=506.54,523.98
XS Rating Curve= 0 ,0
Exp/Cntr(USF)=0,0
Exp/Cntr=0.3,0.1

Type RM Length L Ch R = 1 ,8960    ,169.9,166.3,162
XS GIS Cut Line= 4
2484531.28016281632613.756000862 2484167.4556813 632400.93634056
2484034.11224268632285.2542845452483808.04654543 632163.39074462
#Sta/Elev= 30
       0 2208.94    65.5  2194.5   145.8 2171.17   176.92165.388   223.1 2158.13
   246.2 2147.82   261.5 2143.31   283.3 2133.12  305.672126.244   329.6 2117.42
   338.7 2115.92   354.2 2110.65   417.8 2106.55  437.082102.218   463.1 2102.35
  475.172099.952     483 2099.01  490.872099.952   505.7 2102.72   562.4 2105.34
     576 2109.14  592.08 2108.98   679.1 2121.35   688.2 2125.49   697.3  2126.8
  718.472136.967     741 2147.05   797.3 2176.16   832.6 2195.35   854.8 2210.87
#Mann= 8 ,-1 , 0
       0      .1       0   176.9      .1       0  305.67      .1       0
  437.08     .06       0  475.17    .045       0  490.87     .06       0
  592.08      .1       0  718.47      .1       0
Bank Sta=475.17,490.87
XS Rating Curve= 0 ,0
Exp/Cntr(USF)=0,0
Exp/Cntr=0.3,0.1

Type RM Length L Ch R = 1 ,8793    ,152.2,151.1,150
XS GIS Cut Line= 4
2484607.22410798632351.4844692862484295.50070513632256.996072388
2483977.59581837632148.3785694122483828.35713542632109.523527697
#Sta/Elev= 30
       0 2254.28    63.2 2227.85   142.6 2198.59  171.512186.284  204.882171.231
     219 2164.63   242.9 2147.63   259.6 2142.24  282.072129.574   293.1 2126.95
   305.6 2121.07     314 2118.83   347.7 2116.17   381.5 2097.97  407.552095.643
   415.3 2094.27  421.842095.644   432.2 2098.24   506.42099.089   533.7 2098.64
     559 2104.78   575.9 2105.27  618.962115.535  632.782119.388   660.5 2127.97
     677 2135.19   689.4 2137.39   718.4 2150.54   772.1 2178.73   815.9 2204.32
#Mann= 9 ,-1 , 0
       0      .1       0  171.51      .1       0  204.88      .1       0
  282.07      .1       0  407.55    .045       0  421.84      .1       0
   506.4     .06       0  618.96      .1       0  632.78      .1       0
#XS Ineff= 2 , 0
                          492.93         2101.26
Permanent Ineff=
       F       F
Bank Sta=407.55,421.84
XS Rating Curve= 0 ,0
Exp/Cntr(USF)=0,0
Exp/Cntr=0.3,0.1

Type RM Length L Ch R = 1 ,8642    ,194.5,195.5,195.6
XS GIS Cut Line= 4
2484630.18390536632174.8706433092484330.82347032632098.926698139
2484053.53976354632041.5272046962483863.67990061632002.672162981
#Sta/Elev= 30
       0 2239.48    28.3 2228.65    68.6 2209.94  115.172192.934     148 2180.98
   203.8 2157.94   251.2 2142.25  288.172127.118   329.3 2110.24   350.1    2104
   374.3 2098.87  390.45 2092.56   394.7 2091.24  402.232092.559     411 2094.73
   419.2 2093.43  437.582093.576   488.7 2093.68     505 2094.97   525.4 2097.22
   537.7 2101.38   558.1 2101.62  563.972104.662   574.4 2110.14     652 2137.79
     661 2142.49   676.5 2144.98   684.7 2151.01   729.6 2174.73   785.8 2208.05
#Mann= 7 ,-1 , 0
       0      .1       0  115.17      .1       0  288.17      .1       0
  390.45    .045       0  402.23      .1       0  437.58     .06       0
  563.97      .1       0
Bank Sta=390.45,402.23
XS Rating Curve= 0 ,0
Exp/Cntr(USF)=0,0
Exp/Cntr=0.3,0.1

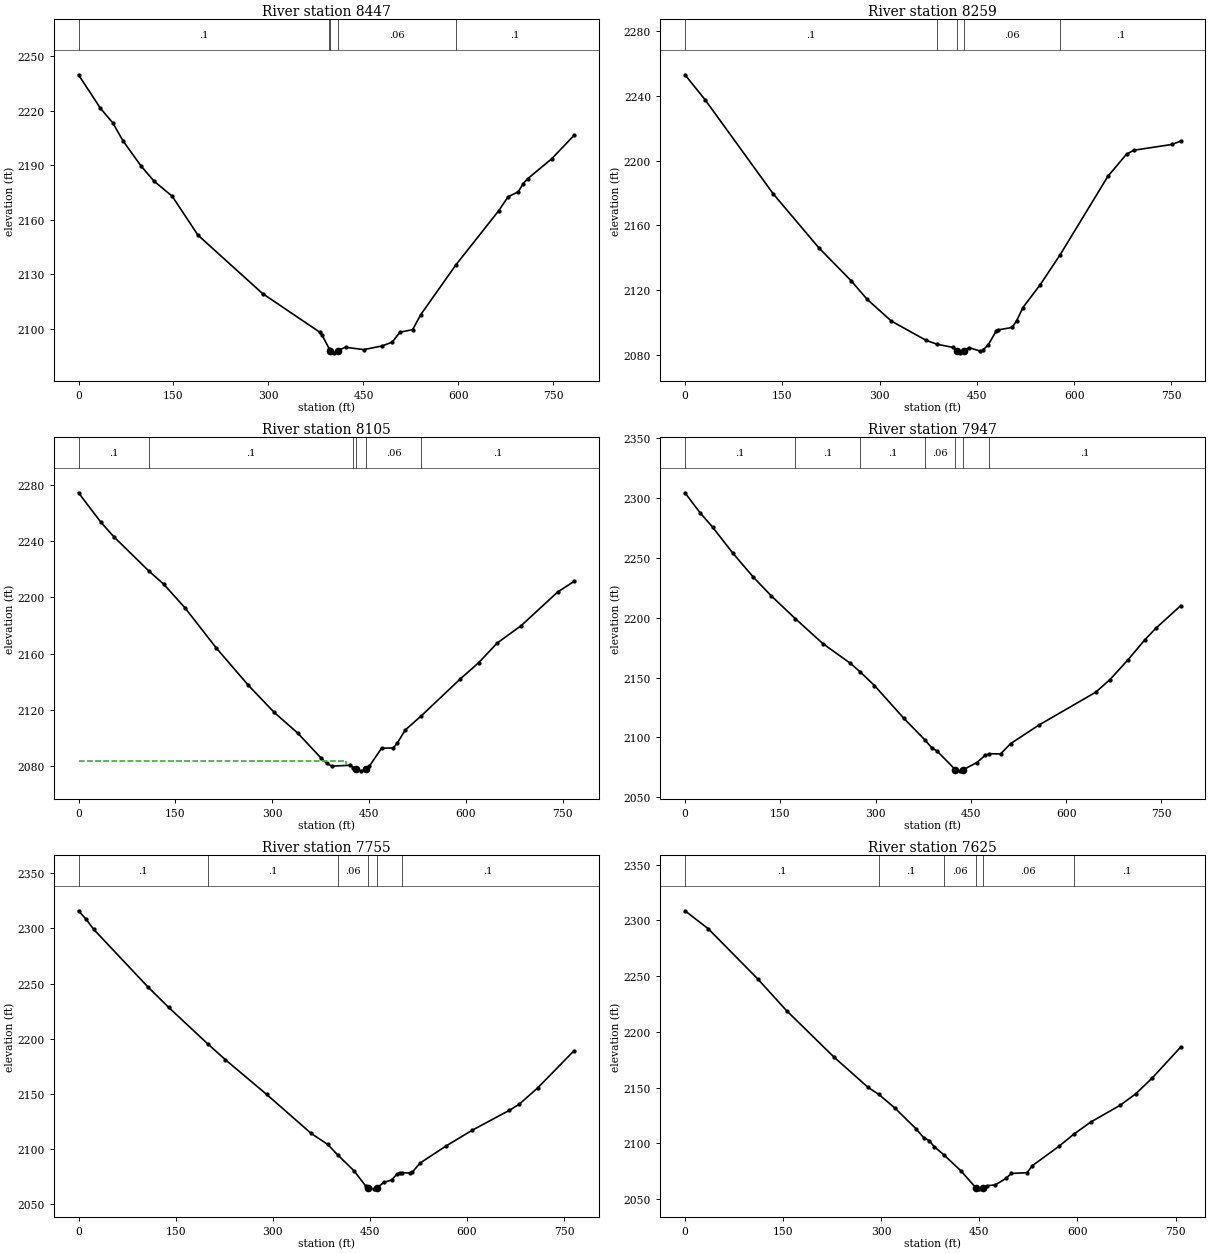
Type RM Length L Ch R = 1 ,8447    ,187.3,187.3,187.7
XS GIS Cut Line= 4
2484663.74053229631970.8816743052484291.08535948631894.937729135
2484116.23767176 631855.199618292483895.47038929631822.526060484
#Sta/Elev= 30
       0 2239.78    34.7  2221.3    54.1  2213.3    70.4  2203.3      99 2189.42
   119.4 2181.14     148 2172.85   188.8 2151.38   290.9  2119.2   380.7 2098.06
   384.8 2096.29  395.812088.943  397.972087.816     404  2086.6  409.282087.815
   421.7 2089.69   450.4 2088.38   479.1 2090.36   495.5 2092.52   507.8 2097.98
   527.7 2099.39   540.6 2107.69  595.85 2134.98   663.4 2164.79   678.4 2172.53
   694.6 2175.33   702.1 2179.76   709.1 2182.45   747.1 2193.43   782.8 2206.46
#Mann= 5 ,-1 , 0
       0      .1       0  395.81     .06       0  397.97    .045       0
  409.28     .06       0  595.85      .1       0
Bank Sta=397.97,409.28
XS Rating Curve= 0 ,0
Exp/Cntr(USF)=0,0
Exp/Cntr=0.3,0.1

Type RM Length L Ch R = 1 ,8259    ,154.2,154.1,153.2
XS GIS Cut Line= 4
2484698.18022836631813.6953691852484372.32771943631727.154594456
2484193.06468606631678.5857923122483957.28522838631626.484713649
#Sta/Elev= 30
       0 2253.15    31.3 2237.57   135.9 2179.61   206.3 2146.21     256 2125.88
   280.8 2114.37   318.1  2100.9   371.9 2088.93  388.912086.501   413.4 2084.58
  419.032082.333   423.4 2081.22     430 2082.37     430 2082.38   438.2 2084.46
   454.8 2082.32     459  2082.9   467.3 2085.95   479.7 2094.57   482.1 2095.33
   504.6 2096.95   511.5 2101.13   521.1 2109.21   547.4 2123.14  578.352141.765
   652.2 2190.41   680.9 2204.07   692.3 2206.51   750.6 2210.05   764.3  2212.1
#Mann= 5 ,-1 , 0
       0      .1       0  388.91     .06       0  419.03    .045       0
     430     .06       0  578.35      .1       0
Bank Sta=419.03,430
XS Rating Curve= 0 ,0
Exp/Cntr(USF)=0,0
Exp/Cntr=0.3,0.1

Type RM Length L Ch R = 1 ,8105    ,159.9,158.7,156.7
XS GIS Cut Line= 4
2484740.56754659631631.783128428 2484421.7795907631572.617496726
   2484158.62499631526.6979019722483986.42650967631488.725929387
#Sta/Elev= 30
       0 2274.16    34.4 2253.42    54.7 2242.95  109.322218.514     132 2209.28
   164.6 2192.68   213.4 2164.02   263.1 2137.53   302.9  2118.4   339.5 2103.67
     376 2085.74   384.2 2082.32   392.3  2080.2   420.7  2080.8  425.462079.218
  429.642077.905   436.9 2076.85  445.462077.906   450.6 2080.25   469.4 2092.89
   487.4 2093.11   493.8 2096.57     506  2105.8  530.562115.713   591.2 2142.02
   619.9 2153.63   648.6 2167.59   685.5 2179.82   742.1 2203.73   767.7 2211.32
#Mann= 6 ,-1 , 0
       0      .1       0  109.32      .1       0  425.46     .06       0
  429.64    .045       0  445.46     .06       0  530.56      .1       0
#XS Ineff= 2 , 0
           414.7 2083.92
Permanent Ineff=
       F       F
Bank Sta=429.64,445.46
XS Rating Curve= 0 ,0
Exp/Cntr(USF)=0,0
Exp/Cntr=0.3,0.1

Type RM Length L Ch R = 1 ,7947    ,192.6,192,189.2
XS GIS Cut Line= 4
2484774.12417353631431.326435944 2484489.7759137631405.717431177
2484261.94407819631395.1206016192483995.25720097631398.652878138
#Sta/Elev= 30
       0 2304.31    23.5 2287.81    43.6 2275.52    75.7 2253.67   107.8 2233.75
   135.9 2218.18  173.532199.267   217.2 2178.28   260.4 2161.88  276.052154.635
   298.3 2143.32   344.5 2115.99  377.632097.961   388.6 2091.27   396.7 2088.71
  425.522073.138   432.7 2072.09  438.46 2073.14   459.5 2079.01   472.7 2085.07
  479.122086.388   496.8 2086.19   512.5 2094.78   556.8  2110.2   646.8 2137.82
   668.8 2148.17   696.8  2164.4   723.8 2181.45   741.5 2191.26   780.3    2210
#Mann= 7 ,-1 , 0
       0      .1       0  173.53      .1       0  276.05      .1       0
  377.63     .06       0  425.52    .045       0  438.46     .06       0
  479.12      .1       0
Bank Sta=425.52,438.46
XS Rating Curve= 0 ,0
Exp/Cntr(USF)=0,0
Exp/Cntr=0.3,0.1

Type RM Length L Ch R = 1 ,7755    ,130.3,129.9,128.6
XS GIS Cut Line= 4
2484766.17655136631203.4946004332484436.79176591631201.728462173
  2484226.621313631216.7406373822484002.32175401631240.583503888
#Sta/Elev= 30
       0 2315.86    11.4 2308.42    23.4  2299.1   107.4 2246.78   139.4 2228.32
  199.48 2195.43   226.8 2181.04   290.5 2149.65   359.5  2114.2   384.8 2104.38
  400.182094.956   425.4  2080.5   443.7 2066.63  447.482065.109   455.8 2064.07
  461.282065.109   471.8 2069.97   483.8 2072.05   491.8 2077.38   495.9 2078.56
  499.89 2078.68   511.9 2078.43   515.8 2079.33   527.9  2087.5   568.1    2103
   608.4  2117.2   665.6 2135.19   680.8 2140.68   709.2 2155.38   765.7 2189.26
#Mann= 6 ,-1 , 0
       0      .1       0  199.48      .1       0  400.18     .06       0
  447.48    .045       0  461.28     .06       0  499.89      .1       0
Bank Sta=447.48,461.28
XS Rating Curve= 0 ,0
Exp/Cntr(USF)=0,0
Exp/Cntr=0.3,0.1

Type RM Length L Ch R = 1 ,7625    ,192.3,193.4,190.4
XS GIS Cut Line= 4
2484737.03527007631025.997705326 2484421.7795907631061.320470521
2484155.97578261631105.473927016 2483987.3095788631133.732139172
#Sta/Elev= 30
       0  2308.7    35.5 2292.62     111  2247.7   155.3 2219.07   227.7 2177.48
     280 2150.17  296.052144.023   320.3 2132.05     353 2113.19   364.9 2105.15
     373 2102.53   381.1    2097  395.392089.937   421.7 2075.41  444.352060.357
   449.9  2059.2  455.13 2060.36   462.2 2061.96   474.4  2062.8   490.6 2068.48
   498.7 2072.98   522.9 2073.68   531.2 2080.06   571.7 2097.36  594.022108.079
   620.2 2119.08     665 2134.11   688.8 2144.31   713.7  2158.3   757.7 2186.33
#Mann= 6 ,-1 , 0
       0      .1       0  296.05      .1       0  395.39     .06       0
  444.35    .045       0  455.13     .06       0  594.02      .1       0
Bank Sta=444.35,455.13
XS Rating Curve= 0 ,0
Exp/Cntr(USF)=0,0
Exp/Cntr=0.3,0.1

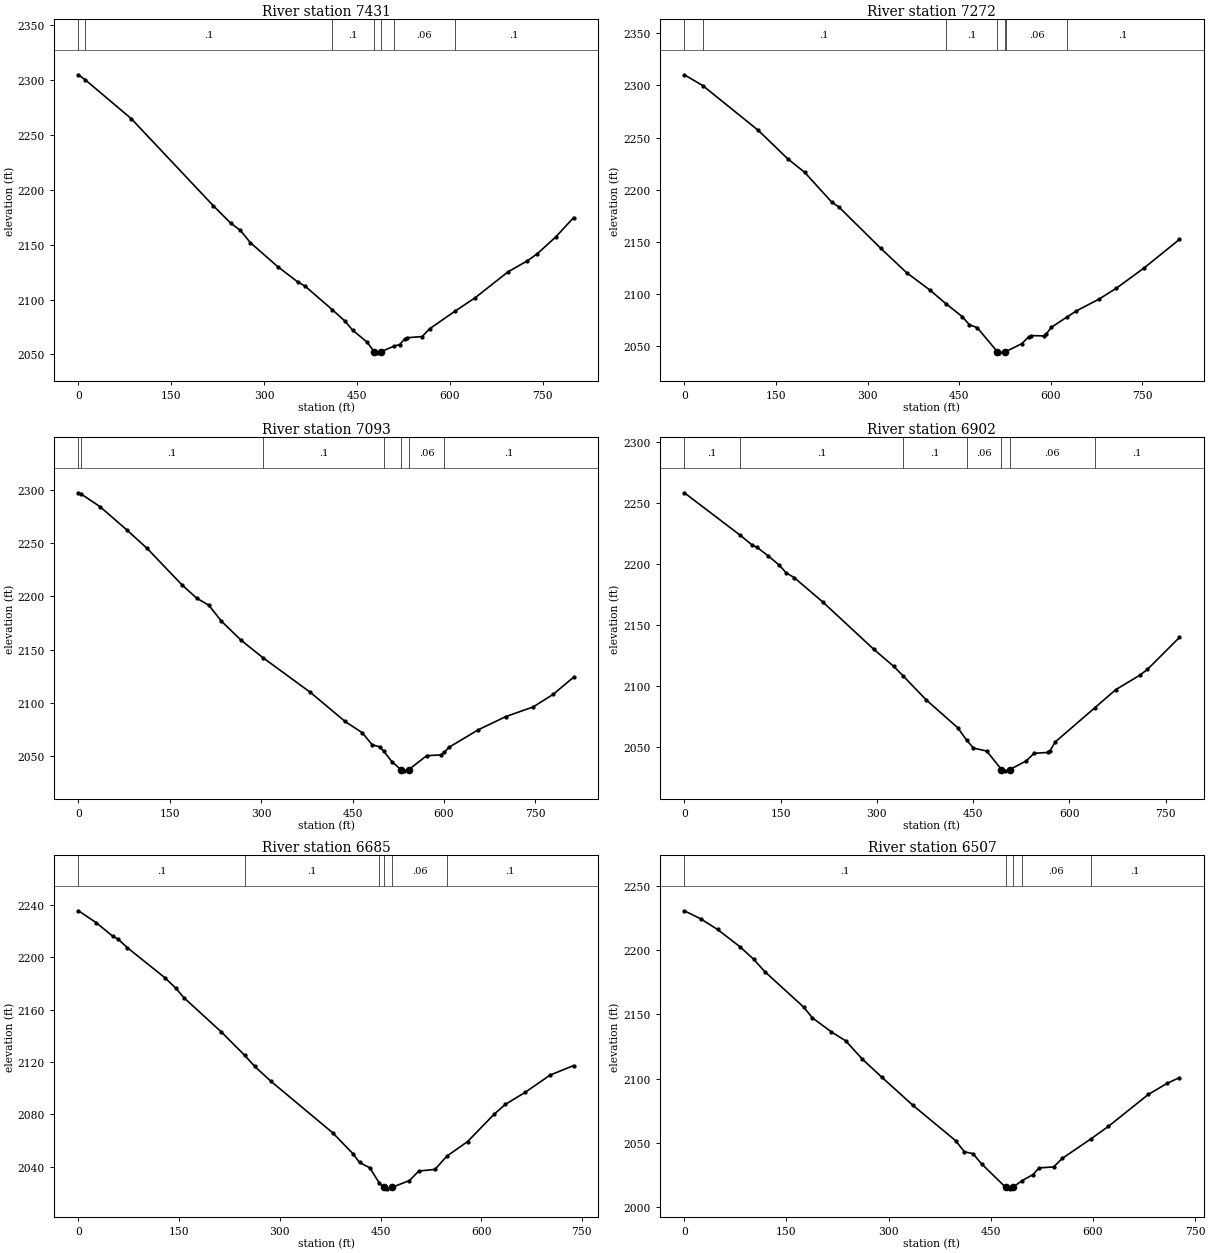
Type RM Length L Ch R = 1 ,7431    ,159.3,159.4,158.4
XS GIS Cut Line= 4
2484723.78923312630860.8637780372484320.22664077630890.888128453
2484155.97578261630912.0817875712483929.02701623630949.170691026
#Sta/Elev= 30
       0 2304.67   11.142300.008    85.3 2264.69   217.6 2185.58   245.9 2169.63
   261.8 2162.88   277.8 2151.79   321.9 2129.99     354 2116.17   366.1 2112.21
  409.872090.891   430.4 2080.47   443.4  2071.9   466.7 2061.06  477.672052.593
   482.8 2051.42  489.722052.594  509.242057.369   519.1 2058.98   527.2 2064.05
   531.2 2065.19   555.4 2066.23   567.5 2073.31  608.582089.372   641.1 2101.58
   694.3 2125.21   725.6 2135.23   741.8  2141.8   771.9 2157.23   800.2 2174.56
#Mann= 7 ,-1 , 0
       0      .1       0   11.14      .1       0  409.87      .1       0
  477.67    .045       0  489.72      .1       0  509.24     .06       0
  608.58      .1       0
Bank Sta=477.67,489.72
XS Rating Curve= 0 ,0
Exp/Cntr(USF)=0,0
Exp/Cntr=0.3,0.1

Type RM Length L Ch R = 1 ,7272    ,177.4,178.8,176.6
XS GIS Cut Line= 4
2484714.95854182630687.7822285792484373.21078856630719.572717255
2484118.88687915 630761.076966362483913.13177189630801.698146335
#Sta/Elev= 30
       0 2310.28   30.152299.933   120.7  2257.1   169.5 2229.56   197.1 2216.59
   241.3  2188.1   253.3 2183.22   321.6 2143.69   363.8 2120.41   402.5 2103.48
  428.13 2090.62   455.2 2078.08   466.7 2070.38   479.5 2067.58  512.192044.641
   515.9 2043.39  525.652044.642  527.452044.891   552.4 2052.16   564.3 2059.01
   567.8 2059.93   588.9 2059.65   592.2 2061.23   600.9 2067.88  626.782077.858
   641.8 2083.62   678.5  2094.8   707.1 2105.31   752.4 2124.68   810.6 2152.24
#Mann= 7 ,-1 , 0
       0      .1       0   30.15      .1       0  428.13      .1       0
  512.19    .045       0  525.65      .1       0  527.45     .06       0
  626.78      .1       0
Bank Sta=512.19,525.65
XS Rating Curve= 0 ,0
Exp/Cntr(USF)=0,0
Exp/Cntr=0.3,0.1

Type RM Length L Ch R = 1 ,7093    ,191.6,190.9,190.4
XS GIS Cut Line= 4
2484657.58883014630492.1762175232484375.10826865630543.687378736
 2483999.5752869630606.8300924822483858.33500615630640.063099716
#Sta/Elev= 30
       0 2297.28    4.752295.944    35.4 2284.25    80.4 2261.88   112.7 2245.06
   169.6 2211.05     194 2198.37     214 2191.73   234.7 2176.79   267.2 2158.78
  302.752142.553   380.8 2109.94   437.6  2082.7     466 2072.07   482.2 2060.79
   494.4 2058.86  501.392054.658   514.7 2044.85  529.432037.439   534.9 2036.28
  542.342037.439   571.8 2050.51   595.8 2051.25   600.72053.561   607.9  2058.2
   656.6 2074.86   701.9 2087.25   746.9 2096.33   779.7 2108.18     813 2124.12
#Mann= 7 ,-1 , 0
       0      .1       0    4.75      .1       0  302.75      .1       0
  501.39     .06       0  529.43    .045       0  542.34     .06       0
   600.7      .1       0
Bank Sta=529.43,542.34
XS Rating Curve= 0 ,0
Exp/Cntr(USF)=0,0
Exp/Cntr=0.3,0.1

Type RM Length L Ch R = 1 ,6902    ,218.5,217.6,215.9
XS GIS Cut Line= 4
2484561.21310916 630287.793223032484189.00342813630375.860692202
2483982.95878328630424.0485526922483810.14714566630463.928161373
#Sta/Elev= 30
       0 2258.13    87.12223.417   105.3 2215.55   113.5 2213.44     130 2206.83
   147.6 2199.13   158.7  2192.7   171.1 2188.83   216.3 2168.57   295.3 2130.12
   326.2 2116.25  340.462108.657   376.9  2088.8   425.9  2066.1  440.022055.773
   450.5 2049.44   471.1 2046.99  494.122031.901   499.8 2030.81  507.27  2031.9
   532.7 2038.93     545 2045.17   566.7 2045.83   569.7 2047.14   577.9 2054.42
  639.122082.155   672.3 2097.22   709.3 2108.86   721.6 2113.74   771.4 2139.87
#Mann= 7 ,-1 , 0
       0      .1       0    87.1      .1       0  340.46      .1       0
  440.02     .06       0  494.12    .045       0  507.27     .06       0
  639.12      .1       0
Bank Sta=494.12,507.27
XS Rating Curve= 0 ,0
Exp/Cntr(USF)=0,0
Exp/Cntr=0.3,0.1

Type RM Length L Ch R = 1 ,6685    ,175.6,177.4,174.8
XS GIS Cut Line= 4
2484436.58933203 630095.041781072484110.90586113630161.507795539
 2483886.5830623630237.9437121782483725.40297721630286.131572668
#Sta/Elev= 30
       0  2235.5    26.4 2226.43    50.9 2216.11      59 2213.85    72.6  2207.4
   128.4 2184.51   144.8 2176.51     157 2169.16   212.9 2142.93  247.622125.069
   262.5 2116.71   286.2 2105.52   379.1 2065.79   408.6 2050.14   418.7 2043.32
     434 2039.25  447.942027.737  454.472024.323   459.3 2023.16  467.252024.325
   493.1 2029.49     507 2036.76   531.2 2038.01  548.672048.056   579.7 2059.27
   619.3 2080.16     636 2087.68   665.2 2096.77   702.8 2110.07   737.6 2117.28
#Mann= 6 ,-1 , 0
       0      .1       0  247.62      .1       0  447.94     .06       0
  454.47    .045       0  467.25     .06       0  548.67      .1       0
Bank Sta=454.47,467.25
XS Rating Curve= 0 ,0
Exp/Cntr(USF)=0,0
Exp/Cntr=0.3,0.1

Type RM Length L Ch R = 1 ,6507    ,171.6,170.6,167
XS GIS Cut Line= 4
2484358.49176503629938.846647067 2484042.7781963630005.312661536
2483806.82384494630083.4102285382483662.26026347630141.567991198
#Sta/Elev= 30
       0 2230.98    24.3 2224.62    48.8 2216.37    81.5 2202.98   101.9 2193.08
     118 2183.54   175.5 2155.64   187.8 2147.49   215.9 2136.42   236.8 2129.52
   261.4 2115.17   290.2 2100.93   335.3 2079.25   398.5 2051.42   411.2 2042.86
   423.8 2041.32   436.4 2033.44  471.792015.073   478.6 2013.87  482.542015.072
   495.82020.239   512.3 2025.05   520.7 2030.21   542.3 2030.97     555 2037.66
  596.692052.736   622.8 2062.68   681.5 2087.63   709.2 2096.32     727 2100.71
#Mann= 5 ,-1 , 0
       0      .1       0  471.79    .045       0  482.54      .1       0
   495.8     .06       0  596.69      .1       0
Bank Sta=471.79,482.54
XS Rating Curve= 0 ,0
Exp/Cntr(USF)=0,0
Exp/Cntr=0.3,0.1

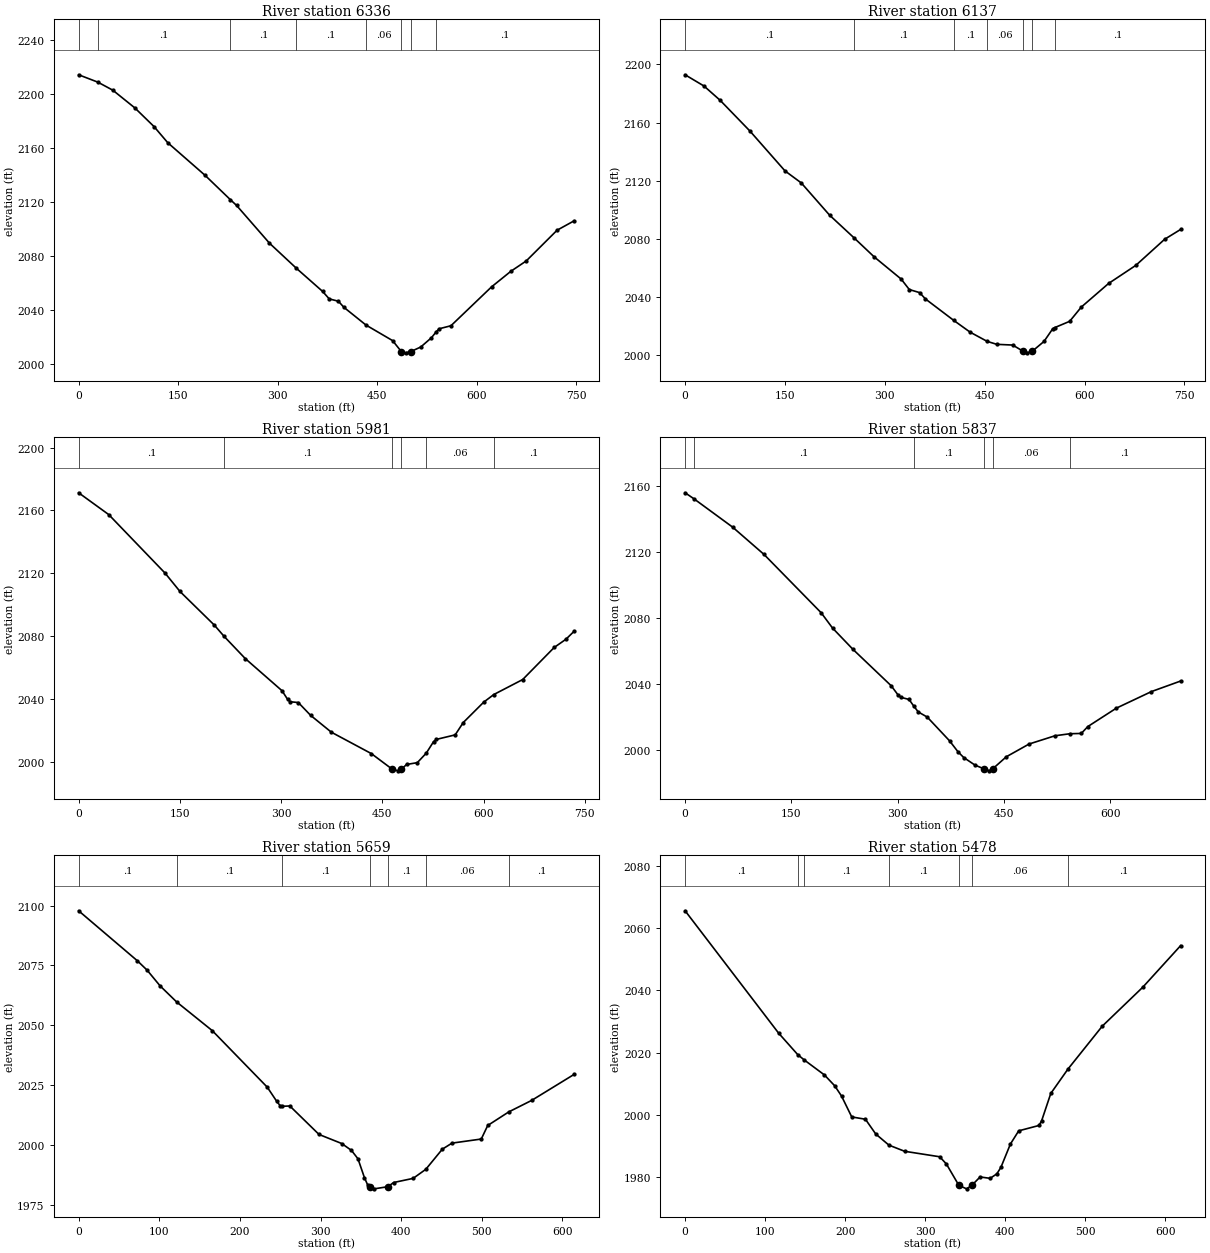
Type RM Length L Ch R = 1 ,6336    ,197,199.5,200.2
XS GIS Cut Line= 4
2484260.45439369629754.4034569162483924.80102062629845.794226811
2483720.41802613629962.1097521322483580.83939574630048.515570941
#Sta/Elev= 30
       0 2214.01   28.912208.572    51.5 2202.63    84.7 2189.54   113.7 2175.71
   134.4 2163.78   190.8 2139.61  228.642121.747   238.1 2117.44   287.8 2089.49
  328.512070.876   367.8 2053.88   377.9 2048.31   391.7  2046.6     400 2042.08
  433.312028.974   473.4 2017.48  486.562009.399   492.9 2008.44  500.912009.398
   515.9 2012.76     532 2019.61   539.32024.064   543.8 2026.26   561.4 2028.47
   622.6  2057.2   651.6 2068.68   674.9 2076.37   721.4 2099.08   747.2 2106.06
#Mann= 8 ,-1 , 0
       0      .1       0   28.91      .1       0  228.64      .1       0
  328.51      .1       0  433.31     .06       0  486.56    .045       0
  500.91     .06       0   539.3      .1       0
Bank Sta=486.56,500.91
XS Rating Curve= 0 ,0
Exp/Cntr(USF)=0,0
Exp/Cntr=0.3,0.1

Type RM Length L Ch R = 1 ,6137    ,149.7,156.1,158.1
XS GIS Cut Line= 4
2484170.72527416629656.3660855742483781.89908951629722.832100043
2483590.80929791629795.9447159592483466.18552078629870.718982236
#Sta/Elev= 30
       0 2192.86    28.4 2185.12    52.7 2175.28    97.4 2154.15   150.1 2126.73
   174.5 2118.48   217.1 2096.27  253.822080.676     284 2067.61   324.6 2052.32
   336.8 2045.13   352.2 2043.03   361.1 2038.64  403.612023.889   428.2  2015.8
   453.72009.491   468.2 2007.44   492.1 2006.95  508.032002.614   513.5 2001.59
  521.322002.615   539.2 2009.46     552 2017.99  555.132018.922   577.7 2023.27
   595.2 2033.08   636.2 2049.32   677.1 2061.77   720.4 2079.72   744.4 2086.48
#Mann= 7 ,-1 , 0
       0      .1       0  253.82      .1       0  403.61      .1       0
   453.7     .06       0  508.03    .045       0  521.32     .06       0
  555.13      .1       0
Bank Sta=508.03,521.32
XS Rating Curve= 0 ,0
Exp/Cntr(USF)=0,0
Exp/Cntr=0.3,0.1

Type RM Length L Ch R = 1 ,5981    ,141.3,143.8,145
XS GIS Cut Line= 4
2484119.21411294629581.5918192962483766.94423626629609.839875445
2483534.31318561629621.4714279772483386.42630342629619.809777616
#Sta/Elev= 30
       0 2171.22    44.6 2157.35     128 2120.16   150.2 2108.44   201.1 2087.04
  215.642079.855   246.8 2065.82   301.4 2045.31   309.5 2039.91   313.5 2038.33
   325.5 2037.82   343.7 2029.68   374.4 2018.97   433.7 2005.35  464.781995.377
   473.8 1994.39  478.261995.377   485.8 1998.44   501.8 1999.59  515.022005.626
   525.8 2012.89     530 2014.38   557.9 2017.26   569.9 2025.12   600.3 2038.12
   615.22042.935   657.9 2052.44   704.6 2072.84   721.9 2078.04   734.2 2083.18
#Mann= 6 ,-1 , 0
       0      .1       0  215.64      .1       0  464.78    .045       0
  478.26      .1       0  515.02     .06       0   615.2      .1       0
Bank Sta=464.78,478.26
XS Rating Curve= 0 ,0
Exp/Cntr(USF)=0,0
Exp/Cntr=0.3,0.1

Type RM Length L Ch R = 1 ,5837    ,177.4,177.9,175.7
XS GIS Cut Line= 4
2484105.36702659629523.6186844532483782.26834515 629484.84684268
2483597.64052718629470.0766172422483414.85898739 629423.91966275
#Sta/Elev= 30
       0 2156.12    12.42152.496    67.1 2135.27   111.4 2118.71     192 2083.35
     208 2074.09   236.8 2061.18   290.8 2039.08   300.8 2033.33   304.8 2032.02
     316 2030.78  322.432026.873     329  2023.2   341.7 2020.07   373.1  2005.7
   385.1 1999.01   393.2 1995.53   409.2 1990.91  421.711988.708   429.3 1987.48
  434.071988.707   453.3 1996.03   485.4 2003.75   521.9 2008.75  543.012009.983
     559 2010.16   568.3 2014.35   608.5  2025.5     658 2035.55   699.2 2041.95
#Mann= 6 ,-1 , 0
       0      .1       0    12.4      .1       0  322.43      .1       0
  421.71    .045       0  434.07     .06       0  543.01      .1       0
Bank Sta=421.71,434.07
XS Rating Curve= 0 ,0
Exp/Cntr(USF)=0,0
Exp/Cntr=0.3,0.1

Type RM Length L Ch R = 1 ,5659    ,178.8,181.3,184.2
XS GIS Cut Line= 4
2484083.21168844629348.222257382 2483850.5806378629324.220641046
  2483595.794249 629296.526468352483472.09361096629283.602521093
#Sta/Elev= 30
       0 2097.81    72.9  2076.9    84.9 2073.01     101 2066.44  121.63 2059.69
   165.7 2047.74   233.9 2024.12   245.7 2018.17   249.8 2016.43  252.63 2016.13
   261.9 2016.26   298.1 2004.36   326.2 2000.58   338.3 1997.71   346.4 1994.19
   354.4 1986.33   358.4 1983.27  360.791982.532   366.5 1981.64  383.481982.535
   390.6 1984.28   414.8 1986.01  430.521989.795     451 1998.21     463 2000.74
   499.3 2002.45   507.3 2008.11  533.492013.801   561.8 2018.59   614.5 2029.47
#Mann= 7 ,-1 , 0
       0      .1       0  121.63      .1       0  252.63      .1       0
  360.79    .045       0  383.48      .1       0  430.52     .06       0
  533.49      .1       0
Bank Sta=360.79,383.48
XS Rating Curve= 0 ,0
Exp/Cntr(USF)=0,0
Exp/Cntr=0.3,0.1

Type RM Length L Ch R = 1 ,5478    ,169.6,171.1,172.6
XS GIS Cut Line= 4
2484073.98029754629259.600904757 2483850.5806378 629176.51838667
2483625.33469987629102.6672594822483492.40267093629047.278914091
#Sta/Elev= 30
       0  2065.6   116.8 2026.27   140.92019.295  149.152017.569   174.2 2012.78
     187  2009.3   195.5 2006.02   208.3 1999.28   225.4 1998.54   238.3 1993.79
  254.781990.208   274.4 1988.23   318.2 1986.47   326.6 1984.15  342.161977.288
   351.8 1976.15  358.471977.289   368.7 1979.97   381.3 1979.53   389.7 1980.98
   394.8 1983.09   406.6 1990.55     417 1994.81   442.4 1996.54   445.6 1998.01
   457.1 2006.84  478.572014.686   521.5  2028.5     572 2040.99   619.4 2054.39
#Mann= 7 ,-1 , 0
       0      .1       0   140.9      .1       0  149.15      .1       0
  254.78      .1       0  342.16    .045       0  358.47     .06       0
  478.57      .1       0
Bank Sta=342.16,358.47
XS Rating Curve= 0 ,0
Exp/Cntr(USF)=0,0
Exp/Cntr=0.3,0.1