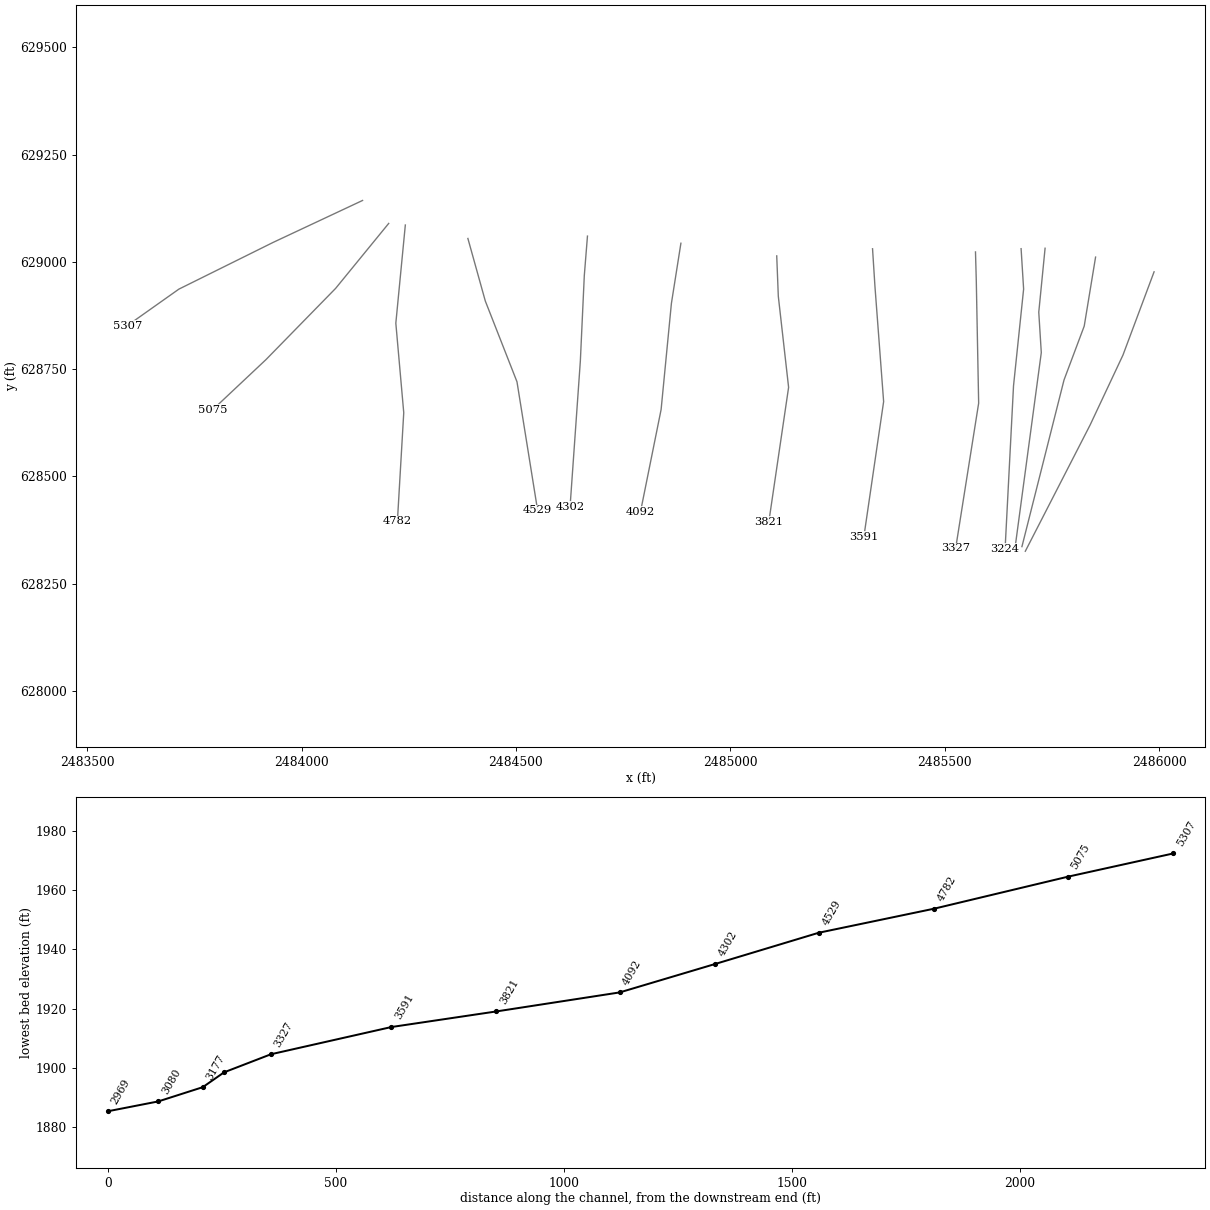
HEC-RAS study SFSBPOTOMC_T1.prj: SFSBPOTOMC_T1

--- SFSBPOTOMC_T1.g01 (geometry) --- (continued)

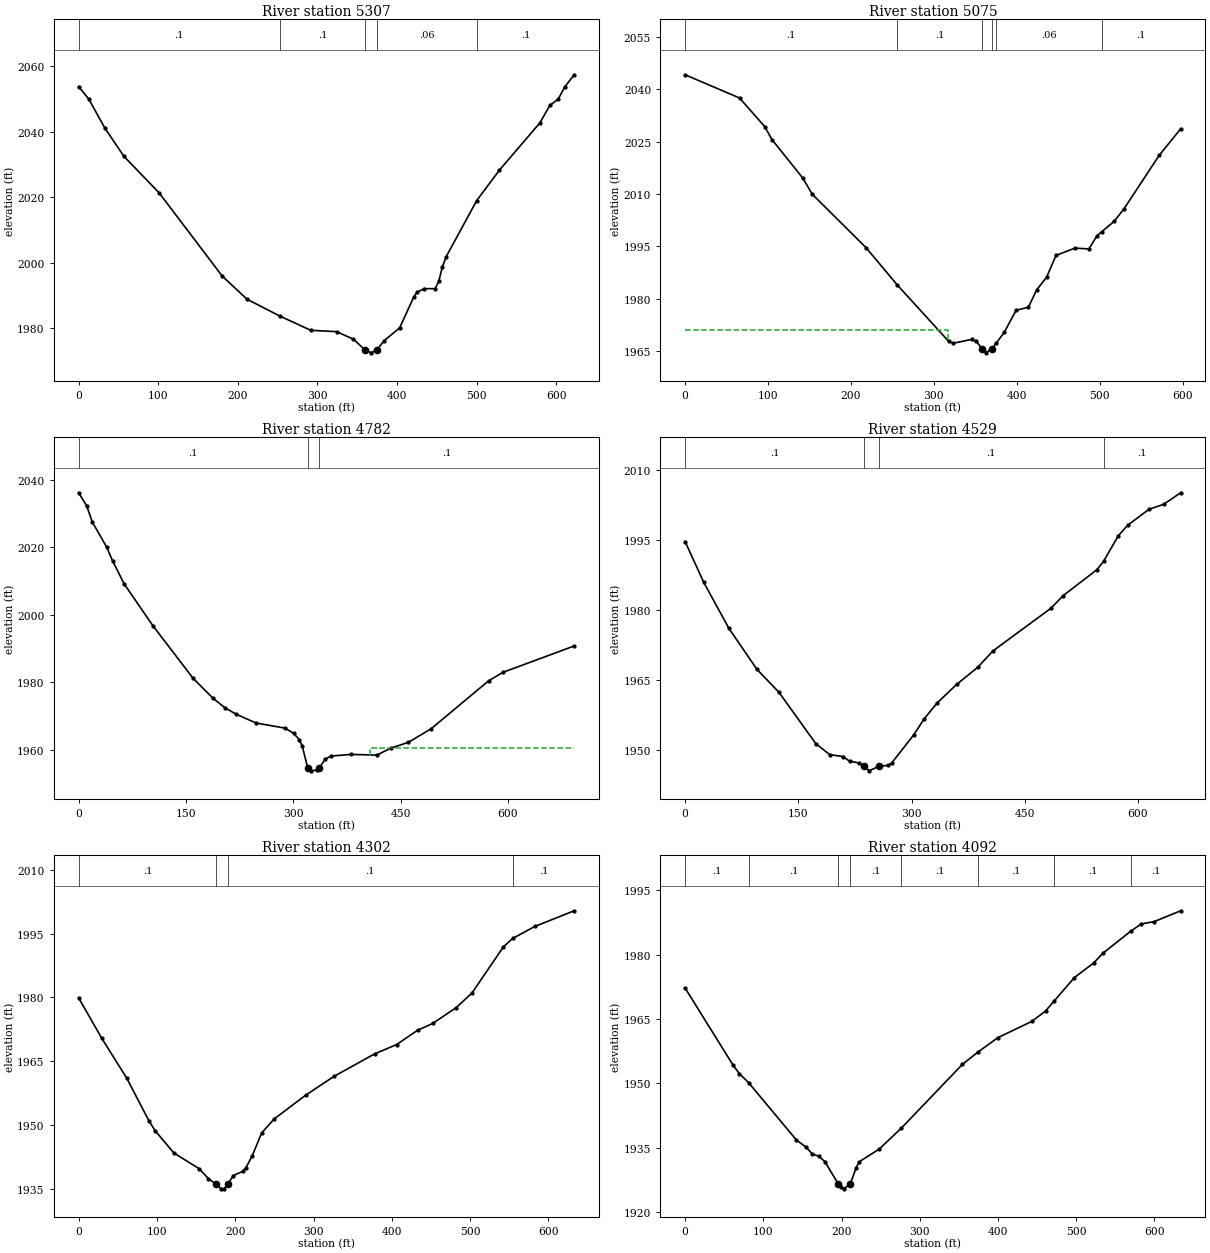
Type RM Length L Ch R = 1 ,5307    ,227.9,231.6,235.2
XS GIS Cut Line= 4
2484142.29259019629143.2853794362483933.66315588629045.432635912
 2483713.9560525628936.5022233092483593.94797082628851.573427043
#Sta/Elev= 30
       0 2053.77    12.8 2049.94      33 2041.07    56.9 2032.46   101.1 2021.32
   180.4 1995.89   211.6 1988.81   252.91983.657   291.7 1979.32   324.1  1978.9
   345.3 1976.59  359.641973.401   367.6 1972.43  375.071973.401   383.8 1976.12
   403.4 1980.05   421.2 1989.53   425.5 1991.02   434.6 1992.04     448 1992.03
   452.5 1994.26   456.9 1998.52   461.5 2001.63  500.13 2018.91   528.6 2028.19
   579.6 2042.67   592.3 2048.07   602.5 2049.88   611.1 2053.73   622.7 2057.37
#Mann= 5 ,-1 , 0
       0      .1       0   252.9      .1       0  359.64    .045       0
  375.07     .06       0  500.13      .1       0
Bank Sta=359.64,375.07
XS Rating Curve= 0 ,0
Exp/Cntr(USF)=0,0
Exp/Cntr=0.3,0.1

Type RM Length L Ch R = 1 ,5075    ,285.2,292.8,305
XS GIS Cut Line= 4
2484203.21977012629089.7433122242484079.51913208628938.348501489
2483917.04665226628772.1834653162483793.34601422628655.867939995
#Sta/Elev= 30
       0 2044.09    65.7 2037.45    96.2 2029.23   104.7 2025.57   141.7 2014.63
   153.5 2009.89   218.3 1994.64   255.51984.083   317.8 1967.87     323 1967.28
   345.6  1968.4   351.4 1967.82   358.1 1965.74   362.6 1964.56  370.05 1965.74
  375.351967.368     385 1970.45   399.3 1976.74     414 1977.58   424.1 1982.57
   436.1 1986.23   447.4 1992.43   470.1  1994.5     487 1994.29   496.9 1998.06
  502.711999.228   517.4 2002.15   529.1 2005.66   571.9 2021.07   597.7 2028.63
#Mann= 6 ,-1 , 0
       0      .1       0   255.5      .1       0   358.1    .045       0
  370.05      .1       0  375.35     .06       0  502.71      .1       0
#XS Ineff= 2 , 0
          316.79 1971.18
Permanent Ineff=
       F       F
Bank Sta=358.1,370.05
XS Rating Curve= 0 ,0
Exp/Cntr(USF)=0,0
Exp/Cntr=0.3,0.1

Type RM Length L Ch R = 1 ,4782    ,249.8,253.8,257.6
XS GIS Cut Line= 4
2484241.99161189629086.0507558652484219.83627373628857.112261583
2484238.29905553628648.4828272772484223.52883009628395.542716658
#Sta/Elev= 30
       0 2036.22    11.2 2032.37    19.2 2027.53    39.3 2020.07    47.4 2016.09
    63.5 2009.25   103.6 1996.87   159.9 1981.25     188 1975.27   204.1 1972.55
   220.2 1970.56   248.3 1967.95   288.5 1966.45   300.5 1964.89   308.4 1963.07
   312.6 1961.12  320.171954.744   324.6 1953.78   332.6 1954.04   336.71954.741
   344.7 1957.24   352.7 1958.16   380.8 1958.65     417 1958.45   436.3  1960.5
   461.1 1962.24   492.7 1966.24   573.3 1980.49   593.3 1982.99   692.8  1990.8
#Mann= 3 ,-1 , 0
       0      .1       0  320.17    .045       0   336.7      .1       0
#XS Ineff= 2 , 0
                          407.97         1960.48
Permanent Ineff=
       F       F
Bank Sta=320.17,336.7
XS Rating Curve= 0 ,0
Exp/Cntr(USF)=0,0
Exp/Cntr=0.3,0.1

Type RM Length L Ch R = 1 ,4529    ,231.2,227.2,221.8
XS GIS Cut Line= 4
2484387.84758809 629054.664026812484428.46570804628908.808050614
2484502.31683523628720.487676285 2484550.3200679628421.390611174
#Sta/Elev= 30
       0 1994.69    24.7 1985.96    57.9 1976.15    95.3 1967.32   124.3 1962.45
   173.2 1951.45   191.7 1949.09   209.3 1948.69   217.9 1947.69   230.8  1947.3
  236.651946.613   244.1 1945.63  256.431946.612   269.5  1946.8   273.8 1947.31
   302.8  1953.3   316.7 1956.73   333.6 1960.09   359.9 1964.14   387.7 1967.77
   407.8 1971.27   484.6  1980.4   501.1 1983.13   545.7 1988.67  554.481990.461
   574.1 1995.94   586.2 1998.14   614.6 2001.58   634.1 2002.65   656.6 2005.12
#Mann= 4 ,-1 , 0
       0      .1       0  236.65    .045       0  256.43      .1       0
  554.48      .1       0
Bank Sta=236.65,256.43
XS Rating Curve= 0 ,0
Exp/Cntr(USF)=0,0
Exp/Cntr=0.3,0.1

Type RM Length L Ch R = 1 ,4302    ,210.2,209.6,209
XS GIS Cut Line= 4
2484666.63559322629060.202861349 2484659.2504805628967.888952364
 2484650.0190896628768.4909089572484626.01747327628428.775723893
#Sta/Elev= 30
       0 1979.92    29.4 1970.46    61.5 1961.04    89.6  1951.1    97.6 1948.75
   121.6  1943.5   153.7 1939.83   165.7  1937.5  175.741936.127   181.7 1935.12
   185.7 1935.08  190.231936.125   197.7 1938.21   209.7  1939.2   213.7 1940.05
   221.7 1942.86   233.8 1948.22   249.8  1951.5   289.8 1957.05   325.9 1961.46
     378 1966.76   406.1 1968.95   432.8  1972.3   452.2  1973.9   482.3 1977.64
   502.3 1981.05   542.4 1991.87  554.251993.852   582.5 1996.67   632.8 2000.35
#Mann= 4 ,-1 , 0
       0      .1       0  175.74    .045       0  190.23      .1       0
  554.25      .1       0
Bank Sta=175.74,190.23
XS Rating Curve= 0 ,0
Exp/Cntr(USF)=0,0
Exp/Cntr=0.3,0.1

Type RM Length L Ch R = 1 ,4092    ,268.8,270.8,273.2
XS GIS Cut Line= 4
2484884.49641843629043.5863577322484862.34108027628903.269216075
2484838.33946393628655.8679399952484790.33623126628417.698054814
#Sta/Elev= 30
       0 1972.21    61.4 1954.24    69.5 1952.26   81.261950.172   142.4 1936.82
   154.5  1935.2   162.5 1933.62   170.6 1933.08   178.7 1931.83  195.941926.571
   198.7 1925.82   202.7 1925.47  211.131926.573   218.8 1930.43   222.8 1931.79
   248.3 1934.74  276.551939.614   354.5 1954.43  374.251957.269   399.8 1960.65
   443.5 1964.46     461 1966.89  471.891969.188   497.7 1974.64   522.2 1978.01
   534.4 1980.34  569.521985.396   583.4 1987.14   599.7 1987.66   633.6 1990.19
#Mann= 8 ,-1 , 0
       0      .1       0   81.26      .1       0  195.94    .045       0
  211.13      .1       0  276.55      .1       0  374.25      .1       0
  471.89      .1       0  569.52      .1       0
Bank Sta=195.94,211.13
XS Rating Curve= 0 ,0
Exp/Cntr(USF)=0,0
Exp/Cntr=0.3,0.1

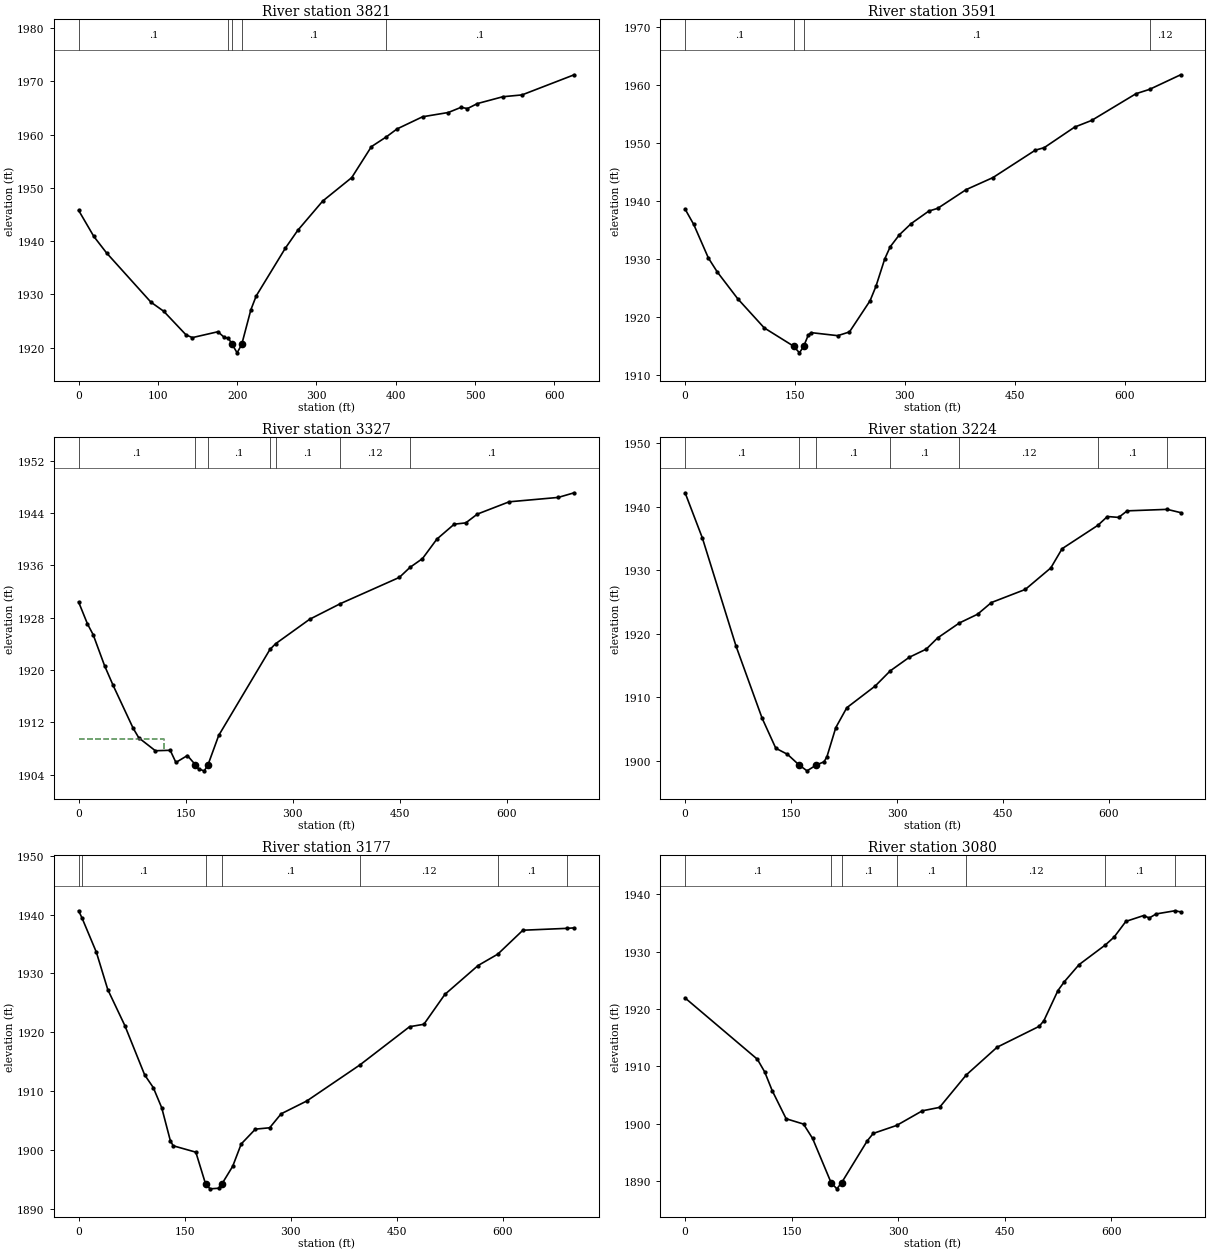
Type RM Length L Ch R = 1 ,3821    ,230.4,229.9,229.1
XS GIS Cut Line= 4
2485107.89607817629014.0459068572485111.58863453628919.885719692
2485135.59025087628707.5637290272485089.43329637628393.696438478
#Sta/Elev= 30
       0 1945.78    19.2 1940.88    35.2  1937.8    91.2 1928.55   107.3 1926.85
   135.5 1922.41   143.5  1921.9   175.7    1923   183.8 1921.93  188.99 1921.76
  193.771920.616   199.9 1919.04  205.731920.619   217.3 1927.14     224 1929.72
   260.7 1938.67   276.4 1942.03   307.9 1947.53   344.5 1951.93   369.3 1957.74
  388.261959.587   401.6 1961.06   433.9 1963.35   466.3 1964.15   482.4 1965.12
   490.5 1964.89   503.1 1965.83   535.2 1967.11   559.3 1967.45   625.1 1971.23
#Mann= 5 ,-1 , 0
       0      .1       0  188.99      .1       0  193.77    .045       0
  205.73      .1       0  388.26      .1       0
Bank Sta=193.77,205.73
XS Rating Curve= 0 ,0
Exp/Cntr(USF)=0,0
Exp/Cntr=0.3,0.1

Type RM Length L Ch R = 1 ,3591    ,264.2,264.4,264
XS GIS Cut Line= 4
2485331.29573791629030.6624104742485336.83457245628943.887336028
2485357.14363243628674.3307217922485310.98667794628358.617153064
#Sta/Elev= 30
       0 1938.55    11.8  1935.9    31.8 1930.12    43.9 1927.72    71.9 1923.09
     108 1918.08     1481914.933   156.1 1913.78  161.941914.935   168.2 1916.87
   172.2 1917.26   208.3 1916.74   224.3 1917.38   252.4 1922.75   260.4 1925.22
   272.5 1929.98   279.9 1932.05   292.5 1934.13   308.6 1936.06   332.6 1938.21
   344.7 1938.68   383.6 1941.91   420.1 1943.98     478 1948.71   490.1 1949.14
   531.7 1952.69   554.8 1953.83   615.4 1958.44  633.861959.184   676.3  1961.7
#Mann= 4 ,-1 , 0
       0      .1       0     148    .045       0  161.94      .1       0
  633.86     .12       0
Bank Sta=148,161.94
XS Rating Curve= 0 ,0
Exp/Cntr(USF)=0,0
Exp/Cntr=0.3,0.1

Type RM Length L Ch R = 1 ,3327    ,105.1,102.9,100.1
XS GIS Cut Line= 4
2485571.31190127629023.2772977552485573.15817945628956.811283286
2485578.69701399628670.6381654332485525.15494678628332.769258548
#Sta/Elev= 30
       0 1930.37    12.4 1927.03    20.4 1925.38    36.4 1920.64    48.4 1917.63
    76.4  1911.1    84.4 1909.62   107.6 1907.65   128.4 1907.72   136.4 1905.86
   152.5 1906.92  163.581905.522   168.1 1904.86   176.2 1904.58  181.451905.521
   196.4 1909.99  268.231923.128  276.14    1924   323.9 1927.74  367.04 1930.13
   449.7 1934.14  464.571935.669   482.1 1937.01   502.3 1939.99   526.6 1942.27
   542.8 1942.47     559 1943.81   603.6 1945.69   672.4 1946.36   694.8 1947.07
#Mann= 7 ,-1 , 0
       0      .1       0  163.58    .045       0  181.45      .1       0
  268.23      .1       0  276.14      .1       0  367.04     .12       0
  464.57      .1       0
#XS Ineff= 2 , 0
           119.5 1909.48
Permanent Ineff=
       F       F
Bank Sta=163.58,181.45
XS Rating Curve= 0 ,0
Exp/Cntr(USF)=0,0
Exp/Cntr=0.5,0.3

Type RM Length L Ch R = 1 ,3224    ,46.6,46.7,51.8
XS GIS Cut Line= 4
2485677.63575865629030.8913526612485683.52288618 628936.69731214
2485659.97437605628711.0240900572485640.35061761628331.304364206
#Sta/Elev= 30
       0 1942.17    24.5 1935.05    72.1 1918.07     109 1906.75   128.4 1902.02
   144.9 1901.07  161.321899.396   172.6 1898.47   185.91899.396   196.7 1899.89
   200.8 1900.69   213.3 1905.26   228.9 1908.39   269.1  1911.8   290.41914.182
   317.4 1916.32   341.4  1917.6   357.5 1919.36  388.321921.712     414 1923.08
   433.6 1924.92   481.6 1926.98   517.7 1930.36   533.7 1933.38  584.421937.063
   597.8 1938.44   613.8  1938.3   625.8 1939.33  682.471939.564   701.5 1939.05
#Mann= 7 ,-1 , 0
       0      .1       0  161.32    .045       0   185.9      .1       0
   290.4      .1       0  388.32     .12       0  584.42      .1       0
  682.47      .1       0
#XS Ineff= 2 , 0
       0     145 1900.84  203.05       0 1900.93
Permanent Ineff=
       F       F
Bank Sta=161.32,185.9
XS Rating Curve= 0 ,0
Exp/Cntr(USF)=0,0
Exp/Cntr=0.5,0.3

Type RM Length L Ch R = 1 ,3177    ,101.4,97.5,86.7
XS GIS Cut Line= 4
2485733.56347021629031.8725405832485718.84565138628882.731976424
2485724.73277891628788.5379359032485663.89912774628336.210303816
#Sta/Elev= 30
       0 1940.64    4.911939.383    25.1  1933.6    41.2 1927.27    65.3 1921.17
    93.4 1912.78   105.5 1910.65   117.5 1907.21   129.6 1901.66   133.6 1900.77
   165.7 1899.68  179.371894.333   185.8 1893.46   197.8 1893.56  202.771894.333
   217.8 1897.28   229.9 1901.08   249.9 1903.59   270.1 1903.82   286.3 1906.19
   322.6 1908.37   397.5 1914.47   467.9 1920.97   488.1 1921.38   517.8 1926.45
   564.7 1931.35  592.611933.282   628.1 1937.34  690.171937.658   700.6 1937.74
#Mann= 7 ,-1 , 0
       0      .1       0    4.91      .1       0  179.37    .045       0
  202.77      .1       0   397.5     .12       0  592.61      .1       0
  690.17      .1       0
Bank Sta=179.37,202.77
XS Rating Curve= 0 ,0
Exp/Cntr(USF)=0,0
Exp/Cntr=0.5,0.3

Type RM Length L Ch R = 1 ,3080    ,111.1,110.4,109.5
XS GIS Cut Line= 4
2485851.30602086629011.2675942192485824.81394697628850.352774995
2485777.71692671628724.760720967 2485679.5981345628336.210303816
#Sta/Elev= 30
       0 1921.92   101.8 1911.24   112.2 1909.01   122.6 1905.79   142.3 1900.87
   166.8 1899.94   179.6 1897.43  205.67 1889.72   213.8 1888.65  220.441889.718
   256.5    1897     265 1898.31  298.021899.706   334.1 1902.25   358.4 1902.85
  395.981908.497   439.5 1913.34   498.8 1916.98   505.4 1917.97   525.2 1923.22
   534.3 1924.77   554.9 1927.73   591.9 1931.16   604.2 1932.52   620.9 1935.27
   645.7 1936.28   653.9 1935.87   663.5 1936.57  689.86 1937.12     698 1936.93
#Mann= 7 ,-1 , 0
       0      .1       0  205.67    .045       0  220.44      .1       0
  298.02      .1       0  395.98     .12       0   591.9      .1       0
  689.86      .1       0
Bank Sta=205.67,220.44
XS Rating Curve= 0 ,0
Exp/Cntr(USF)=0,0
Exp/Cntr=0.3,0.1

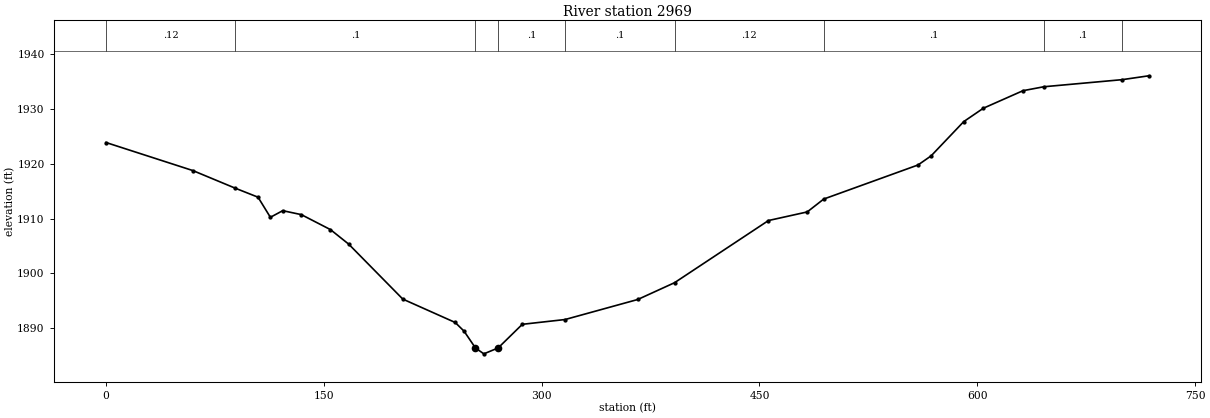
Type RM Length L Ch R = 1 ,2969    ,122.1,119.9,116.8
XS GIS Cut Line= 4
2485987.69114203628976.926016946 2485915.0832358 628782.65080837
2485838.55057788628619.7736133022485687.44763787628325.417236674
#Sta/Elev= 30
       0  1923.9    59.8 1918.78   88.971915.568   104.7 1913.92   113.2 1910.25
   121.7 1911.46   134.5 1910.74   154.6    1908   167.1 1905.36   204.4 1895.32
   240.5 1891.05   246.6 1889.46  254.421886.401   260.2 1885.33  270.031886.403
   286.7 1890.72  316.131891.592   366.2 1895.25   391.5 1898.31   456.2 1909.66
   482.9 1911.23  494.26 1913.58   559.2  1919.8   568.2 1921.46   590.7 1927.72
   604.2 1930.16   631.5 1933.36  645.881934.078  699.771935.371   718.2 1936.08
#Mann= 9 ,-1 , 0
       0     .12       0   88.97      .1       0  254.42    .045       0
  270.03      .1       0  316.13      .1       0   391.5     .12       0
  494.26      .1       0  645.88      .1       0  699.77      .1       0
Bank Sta=254.42,270.03
XS Rating Curve= 0 ,0
Exp/Cntr(USF)=0,0
Exp/Cntr=0.3,0.1