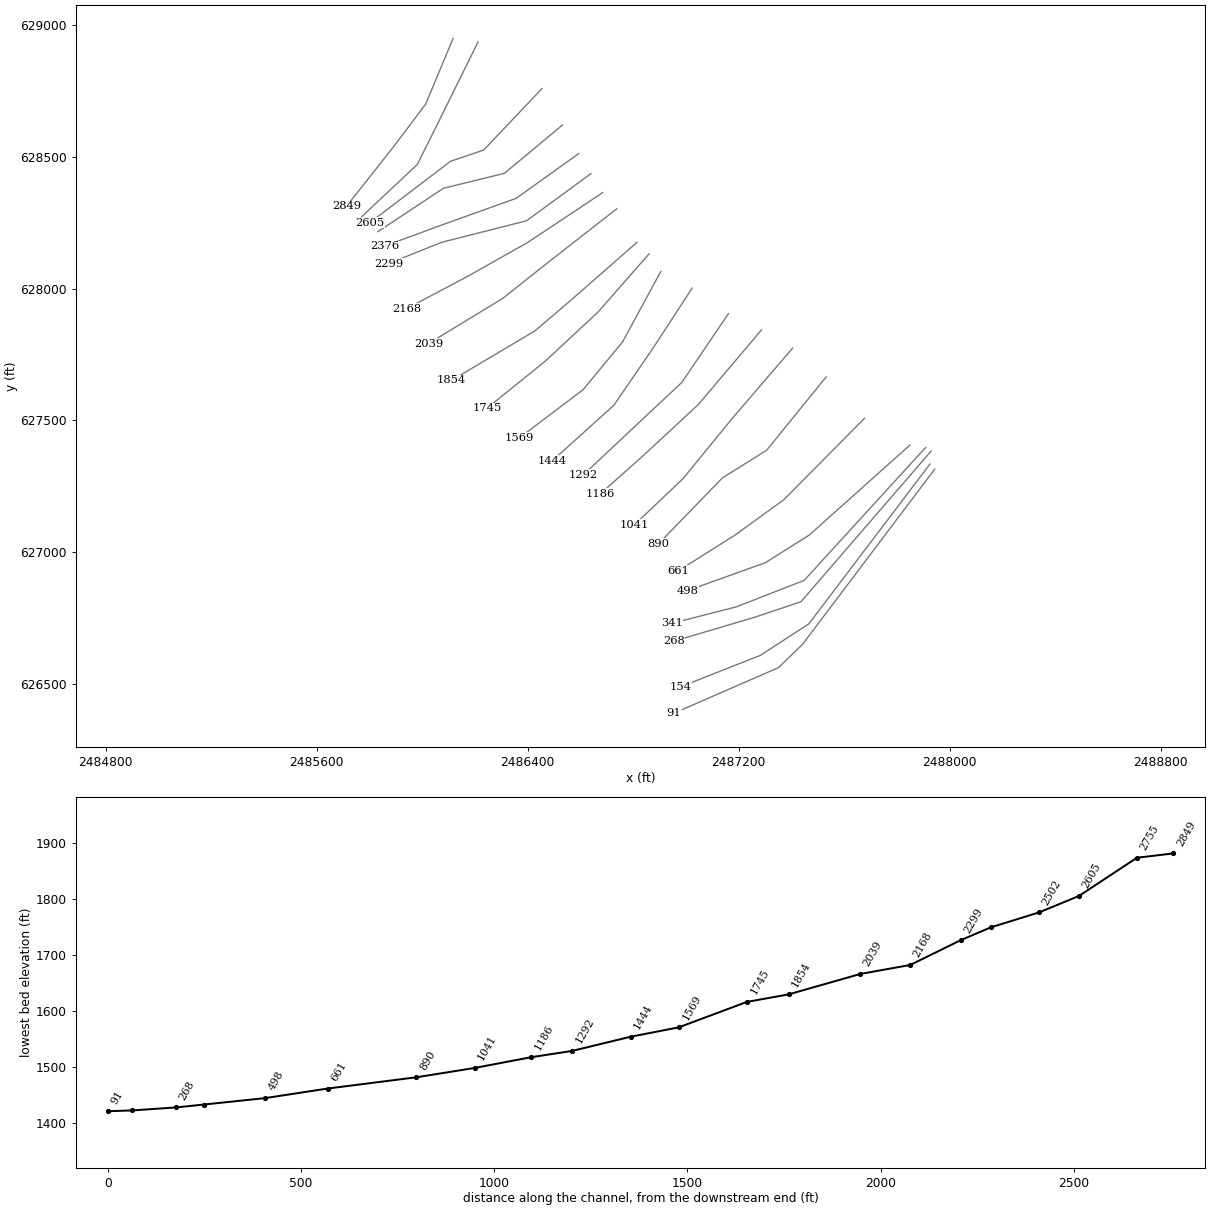
HEC-RAS study SFSBPOTOMC_T1.prj: SFSBPOTOMC_T1

--- SFSBPOTOMC_T1.g01 (geometry) --- (continued)

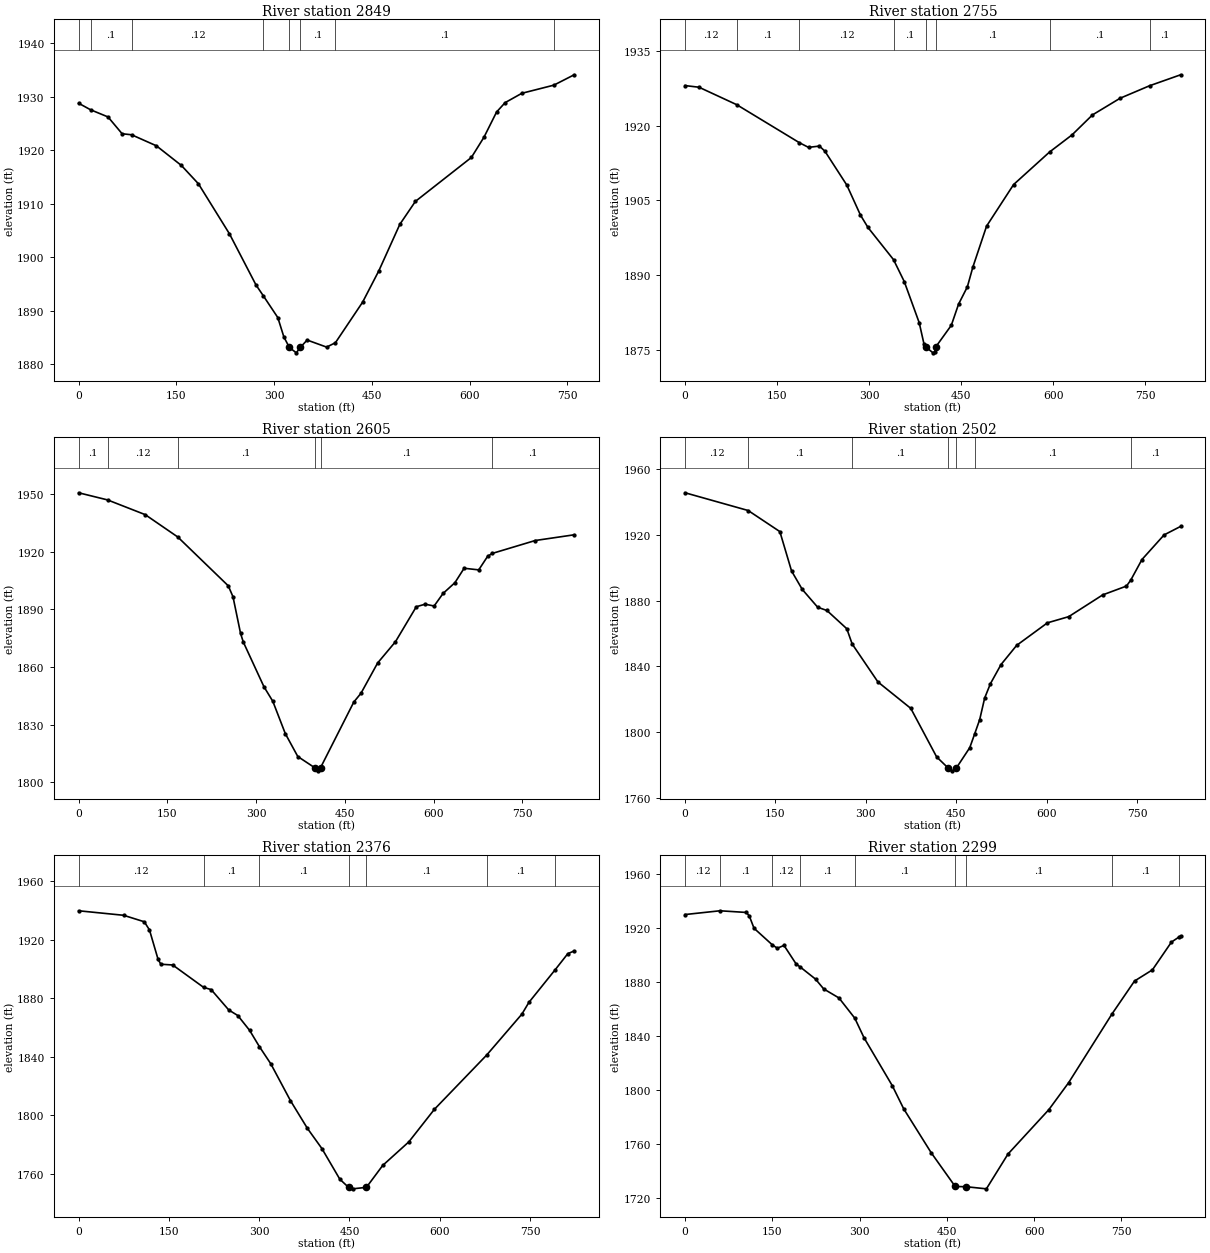
Type RM Length L Ch R = 1 ,2849    ,94.6,94.5,98.7
XS GIS Cut Line= 4
2486117.20794775628948.4715672052486013.20202801628699.249834992
2485893.49710151628540.2973916132485712.95852385628311.680605764
#Sta/Elev= 30
       0  1928.8   18.271927.584    45.1 1926.24    66.7  1923.1   81.24 1922.91
   119.3 1920.85   157.7 1917.17   183.8 1913.75   231.4  1904.4   272.1 1894.85
  283.351892.822   305.6 1888.75   314.9 1885.13  323.341883.163     334 1882.16
  339.981883.164   350.6 1884.55   380.5 1883.23  393.98 1884.05   435.7 1891.63
   460.6 1897.49   492.8 1906.17   516.7 1910.46   602.6 1918.67   621.9 1922.45
   641.3 1927.17   654.3 1928.91     680 1930.66  729.121932.182   760.3 1934.12
#Mann= 8 ,-1 , 0
       0     .12       0   18.27      .1       0   81.24     .12       0
  283.35      .1       0  323.34    .045       0  339.98      .1       0
  393.98      .1       0  729.12      .1       0
Bank Sta=323.34,339.98
XS Rating Curve= 0 ,0
Exp/Cntr(USF)=0,0
Exp/Cntr=0.3,0.1

Type RM Length L Ch R = 1 ,2755    ,156.4,150,142
XS GIS Cut Line= 4
2486211.85240651628935.2680323742486049.72091427628607.031236795
2485981.37136361628470.3321354882485770.75937613 628272.43634348
#Sta/Elev= 30
       0 1928.03    22.7  1927.7   84.241924.191  186.491916.555   201.2 1915.63
   219.1 1915.89     228 1914.85   263.6 1908.07   285.9 1902.04   298.1 1899.56
  339.781893.098   357.3  1888.7   381.7 1880.43   389.3 1876.26  392.57 1875.55
   404.2 1874.39   407.2 1874.61   408.5 1875.55     434 1879.91   445.9 1884.18
   460.2 1887.64   469.1 1891.58   491.5 1899.82   535.6 1908.17  594.361914.715
   630.8 1918.13   664.1 1922.14   709.2 1925.49  757.231927.996   807.9  1930.2
#Mann= 8 ,-1 , 0
       0     .12       0   84.24      .1       0  186.49     .12       0
  339.78      .1       0  392.57    .045       0   408.5      .1       0
  594.36      .1       0  757.23      .1       0
Bank Sta=392.57,408.5
XS Rating Curve= 0 ,0
Exp/Cntr(USF)=0,0
Exp/Cntr=0.3,0.1

Type RM Length L Ch R = 1 ,2605    ,102.4,102.8,104
XS GIS Cut Line= 4
2486454.30394206628758.3358654262486232.99155519628525.031181728
2486107.61754292628482.5130384372485802.35907827 628250.29856354
#Sta/Elev= 30
       0 1950.56   48.941946.845   112.5  1939.2  167.521927.589   252.9  1902.2
   260.9  1896.5   273.7 1877.43   278.3 1872.99   313.2 1849.75   328.2 1842.17
   349.3 1825.38   370.4 1813.48  398.771807.714   404.2 1806.04  408.911807.712
   465.1 1841.81   477.2 1846.36   505.3 1862.08   535.5 1873.16   570.7 1891.34
   585.7 1892.65   600.8 1891.71   615.9 1898.23     636 1903.85   651.5 1911.33
   676.2 1910.49   691.3 1917.56  698.851919.021   771.7 1925.75   837.5 1928.72
#Mann= 6 ,-1 , 0
       0      .1       0   48.94     .12       0  167.52      .1       0
  398.77    .045       0  408.91      .1       0  698.85      .1       0
Bank Sta=398.77,408.91
XS Rating Curve= 0 ,0
Exp/Cntr(USF)=0,0
Exp/Cntr=0.3,0.1

Type RM Length L Ch R = 1 ,2502    ,126.7,125.7,126
XS GIS Cut Line= 4
2486531.70876703 628619.879347532486311.48658896628436.724268739
2486080.36232286628380.0334110182485831.79471593628215.411881866
#Sta/Elev= 30
       0 1945.34  104.681934.582   157.3 1921.79   176.7 1897.92   194.5 1886.71
   220.1 1875.91   235.4 1873.95   268.4 1862.89  277.291853.648   320.1  1830.6
   374.6 1814.59   417.5 1785.17  437.171778.221   443.7 1776.71  449.851778.222
   472.5 1790.77  480.451798.927     489 1807.81   497.2 1820.85   506.8 1829.57
   524.4 1841.18   550.3 1852.79   601.4 1866.47   636.7 1870.21   693.1  1883.4
   732.6 1888.77   739.71892.368   758.3 1904.86     795 1919.78   822.5 1924.95
#Mann= 7 ,-1 , 0
       0     .12       0  104.68      .1       0  277.29      .1       0
  437.17    .045       0  449.85      .1       0  480.45      .1       0
   739.7      .1       0
Bank Sta=437.17,449.85
XS Rating Curve= 0 ,0
Exp/Cntr(USF)=0,0
Exp/Cntr=0.3,0.1

Type RM Length L Ch R = 1 ,2376    ,79.2,77.9,78.3
XS GIS Cut Line= 4
2486593.85066876628511.9486760992486356.18514985628341.876102936
2486076.00148765628241.5768931222485856.86951839628160.901441749
#Sta/Elev= 30
       0 1939.92    74.7 1936.84   109.1  1932.4   117.7 1926.83     132 1906.72
   136.6 1903.36   156.3 1902.85  207.641887.547   220.2 1886.02   249.5 1872.06
   264.5 1868.27   284.2 1858.09  300.231847.093   319.3 1835.27     352 1810.05
   380.2 1791.07   404.2 1777.31     434 1756.34  448.491750.773   455.2 1749.75
  478.181750.772   505.3 1765.77   548.7 1781.89   591.2 1804.16   677.91841.188
   736.6 1869.28   748.1 1877.22  791.921899.636   812.8 1910.58   823.4 1912.44
#Mann= 7 ,-1 , 0
       0     .12       0  207.64      .1       0  300.23      .1       0
  448.49    .045       0  478.18      .1       0   677.9      .1       0
  791.92      .1       0
Bank Sta=448.49,478.18
XS Rating Curve= 0 ,0
Exp/Cntr(USF)=0,0
Exp/Cntr=0.3,0.1

Type RM Length L Ch R = 1 ,2299    ,124.2,130.4,133.3
XS GIS Cut Line= 4
2486639.63943846628435.6340599362486395.43266674628256.839816354
2486072.73086125628175.0741561792485872.13244162628094.398704807
#Sta/Elev= 30
       0 1929.95   59.951932.735   105.2  1931.5   110.2 1929.06   118.5 1919.78
  150.221907.382   158.6 1905.01     170 1907.09   190.9 1893.31   197.81891.123
   224.2 1882.13   238.2 1874.86   264.5 1868.16  291.711853.172   307.5 1838.74
   356.2 1803.14   375.7 1786.09     423 1753.53   464.3 1728.51   483.3 1728.33
   517.9 1726.77     555 1752.53   625.2  1785.4   659.3 1805.42  733.811856.308
   772.5 1880.69   803.3 1888.98     836 1909.55  849.821913.524   851.8 1913.78
#Mann= 9 ,-1 , 0
       0     .12       0   59.95      .1       0  150.22     .12       0
   197.8      .1       0  291.71      .1       0   464.3    .045       0
   483.3      .1       0  733.81      .1       0  849.82     .12       0
Bank Sta=464.3,483.3
XS Rating Curve= 0 ,0
Exp/Cntr(USF)=0,0
Exp/Cntr=0.3,0.1

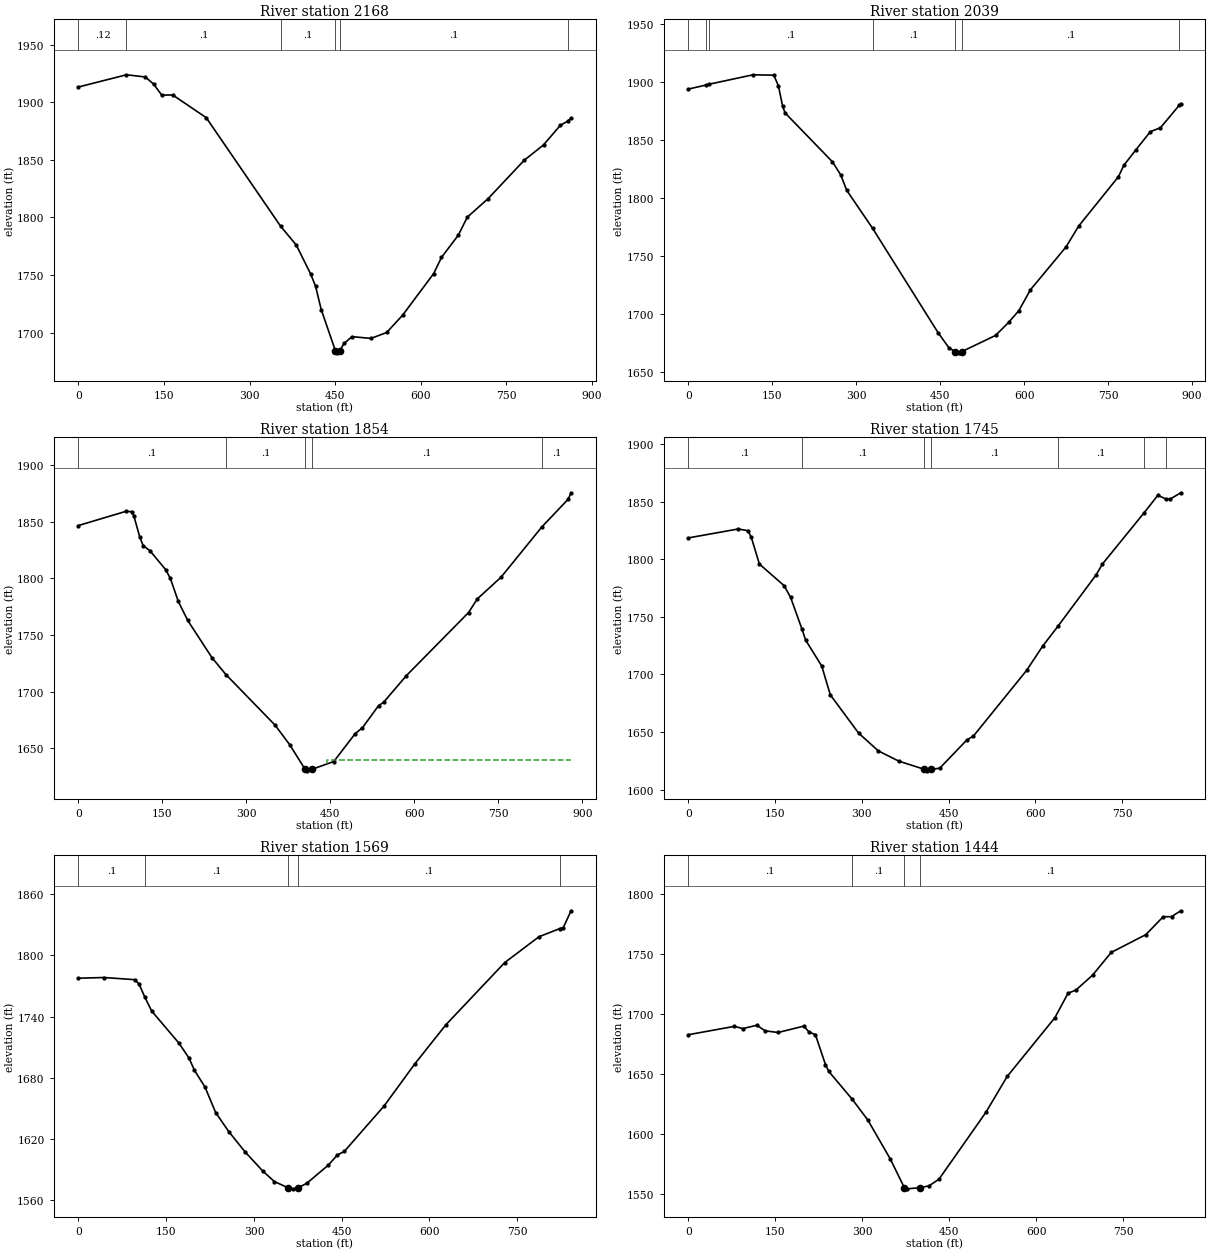
Type RM Length L Ch R = 1 ,2168    ,127.6,129.4,130.7
XS GIS Cut Line= 4
2486684.33799936628363.6802789832486398.70329314628173.983947377
2486168.66923585  628044.24909992485941.90580497627924.326131643
#Sta/Elev= 30
       0 1913.24   84.171923.835   117.2 1921.93   131.6 1915.78     146  1906.2
   165.2 1906.31   223.9 1886.62  354.151792.533   381.8 1776.03   406.8 1751.15
   415.6 1740.32   425.5 1720.12  450.451684.181   453.8 1682.51  457.761684.185
   465.5 1690.64   479.5 1696.57   512.8 1695.02   540.3 1700.19   568.3 1715.25
   622.7 1751.34   636.3  1765.3     666 1784.76   681.6 1800.27   717.8 1816.21
   781.2 1849.56   815.2 1862.98   844.5 1879.87  857.371883.549   863.5 1886.15
#Mann= 6 ,-1 , 0
       0     .12       0   84.17      .1       0  354.15      .1       0
  450.45    .045       0  457.76      .1       0  857.37      .1       0
Bank Sta=450.45,457.76
XS Rating Curve= 0 ,0
Exp/Cntr(USF)=0,0
Exp/Cntr=0.3,0.1

Type RM Length L Ch R = 1 ,2039    ,184.1,185.1,184.8
XS GIS Cut Line= 4
2486737.75823067628302.6285860522486483.73957973628104.210584028
2486304.94533614627962.4834397252486023.67146514627791.320657759
#Sta/Elev= 30
       0 1894.15   32.331897.714   36.721898.299   115.9 1906.52     153 1906.17
   161.2 1896.79   168.5 1879.66   172.9 1873.64   257.6 1831.36   272.5    1820
     283 1806.83  329.141774.048   446.1 1683.93   466.3 1670.31  477.221667.538
   483.4  1666.4  488.961667.538   548.9 1681.43   572.2 1692.67   590.5 1702.86
   611.3 1720.92   674.8 1757.88   697.3 1775.87   768.4 1818.52   777.8  1828.2
   799.2 1841.52   825.4 1857.41   843.4 1860.78  876.831880.108   879.7 1881.42
#Mann= 7 ,-1 , 0
       0      .1       0   32.33     .12       0   36.72      .1       0
  329.14      .1       0  477.22    .045       0  488.96      .1       0
  876.83      .1       0
Bank Sta=477.22,488.96
XS Rating Curve= 0 ,0
Exp/Cntr(USF)=0,0
Exp/Cntr=0.3,0.1

Type RM Length L Ch R = 1 ,1854    ,107.8,108.4,108.7
XS GIS Cut Line= 4
2486814.07284683628175.0741561792486558.96398709627951.581351702
2486427.04872201627839.2898450622486110.88816933627651.773931061
#Sta/Elev= 30
       0 1846.73    84.2 1859.16    94.8 1859.01    98.9 1855.24   109.5 1836.53
   115.6 1828.95   127.8 1824.36   155.6 1807.81   164.1 1800.02   178.2 1779.81
   195.2  1762.8   238.4 1729.99  263.311715.061   351.2 1670.32   377.3 1653.07
  404.971631.199   408.1 1629.93  416.67  1631.2   456.1 1638.18   494.5 1662.91
   507.2 1667.96     536 1687.48     545 1690.48   585.9 1714.12   696.8 1769.78
   712.7 1781.98   754.6 1800.88  828.071845.629   874.9 1869.99     880 1875.65
#Mann= 5 ,-1 , 0
       0      .1       0  263.31      .1       0  404.97    .045       0
  416.67      .1       0  828.07      .1       0
#XS Ineff= 2 , 0
                          444.32          1639.2
Permanent Ineff=
       F       F
Bank Sta=404.97,416.67
XS Rating Curve= 0 ,0
Exp/Cntr(USF)=0,0
Exp/Cntr=0.3,0.1

Type RM Length L Ch R = 1 ,1745    ,175,176.1,176.8
XS GIS Cut Line= 4
2486859.86161653628131.4658040862486665.80444972627910.153417213
2486465.20603009627723.7277120152486244.98385202627546.023677235
#Sta/Elev= 30
       0 1818.48    86.6 1826.25   103.2 1824.74   108.9 1819.23     123 1795.81
   165.7 1777.08   176.9 1766.94  196.381739.691   202.9 1729.85   230.8 1707.29
   245.5 1682.38   294.3 1649.23   328.5  1633.7   363.8 1624.83  408.261617.682
   413.2 1616.39  419.881617.682   434.7 1618.71   481.3 1643.07     493 1646.63
   584.8 1703.55   612.5 1724.58  638.861741.809     705 1786.48   715.6  1795.7
  787.611840.188   811.6 1855.46  824.941852.408   832.2 1852.02   851.2 1857.65
#Mann= 7 ,-1 , 0
       0      .1       0  196.38      .1       0  408.26    .045       0
  419.88      .1       0  638.86      .1       0  787.61      .1       0
  824.94      .1       0
Bank Sta=408.26,419.88
XS Rating Curve= 0 ,0
Exp/Cntr(USF)=0,0
Exp/Cntr=0.3,0.1

Type RM Length L Ch R = 1 ,1569    ,123,124.8,124.7
XS GIS Cut Line= 4
2486904.56017743628064.9630671442486759.56240672627797.861910573
 2486610.2038008627616.8872493862486368.17744668627433.732170595
#Sta/Elev= 30
       0 1777.66    43.3 1778.35      96 1776.24   103.2 1772.29  113.541758.957
   125.2 1745.37   171.5 1714.09     189 1699.27   198.1  1687.4   216.3  1670.8
   234.5 1645.79   257.2 1626.88   284.5 1607.41   315.1 1588.32     335 1578.04
  358.641571.868   366.3 1570.91  375.481571.868   390.8 1576.57   427.1  1594.2
   442.6 1604.15   454.4 1607.62   522.6 1652.35     575 1693.57     628 1731.89
   728.5  1792.9   787.1 1818.31   822.7 1826.34   828.8 1827.32   842.1 1843.85
#Mann= 5 ,-1 , 0
       0      .1       0  113.54      .1       0  358.64    .045       0
  375.48      .1       0   822.7      .1       0
Bank Sta=358.64,375.48
XS Rating Curve= 0 ,0
Exp/Cntr(USF)=0,0
Exp/Cntr=0.3,0.1

Type RM Length L Ch R = 1 ,1444    ,153.6,152,142.9
XS GIS Cut Line= 4
2487023.39293688628001.7309566092486878.39516617627779.328360934
2486726.85614265627558.0159740612486492.46125015627346.515466408
#Sta/Elev= 30
       0 1682.73    79.8 1689.74    94.1 1687.86   118.4 1690.66   132.6 1685.99
     155  1684.6   199.2  1689.9   208.7 1684.79   219.3 1682.89   236.7 1657.77
   242.1  1652.3  282.92  1628.8   309.7 1611.54   348.4 1579.07  372.751555.056
   377.5 1554.07  400.311555.055   415.2 1556.58   432.5 1562.16   513.3 1617.93
     550 1647.87   632.3 1696.95     655 1717.38   668.6 1720.03   697.4 1732.54
   729.4 1751.43   789.2 1766.32     819 1781.23   833.4 1781.32   849.4 1786.22
#Mann= 4 ,-1 , 0
       0      .1       0  282.92      .1       0  372.75    .045       0
  400.31      .1       0
Bank Sta=372.75,400.31
XS Rating Curve= 0 ,0
Exp/Cntr(USF)=0,0
Exp/Cntr=0.3,0.1

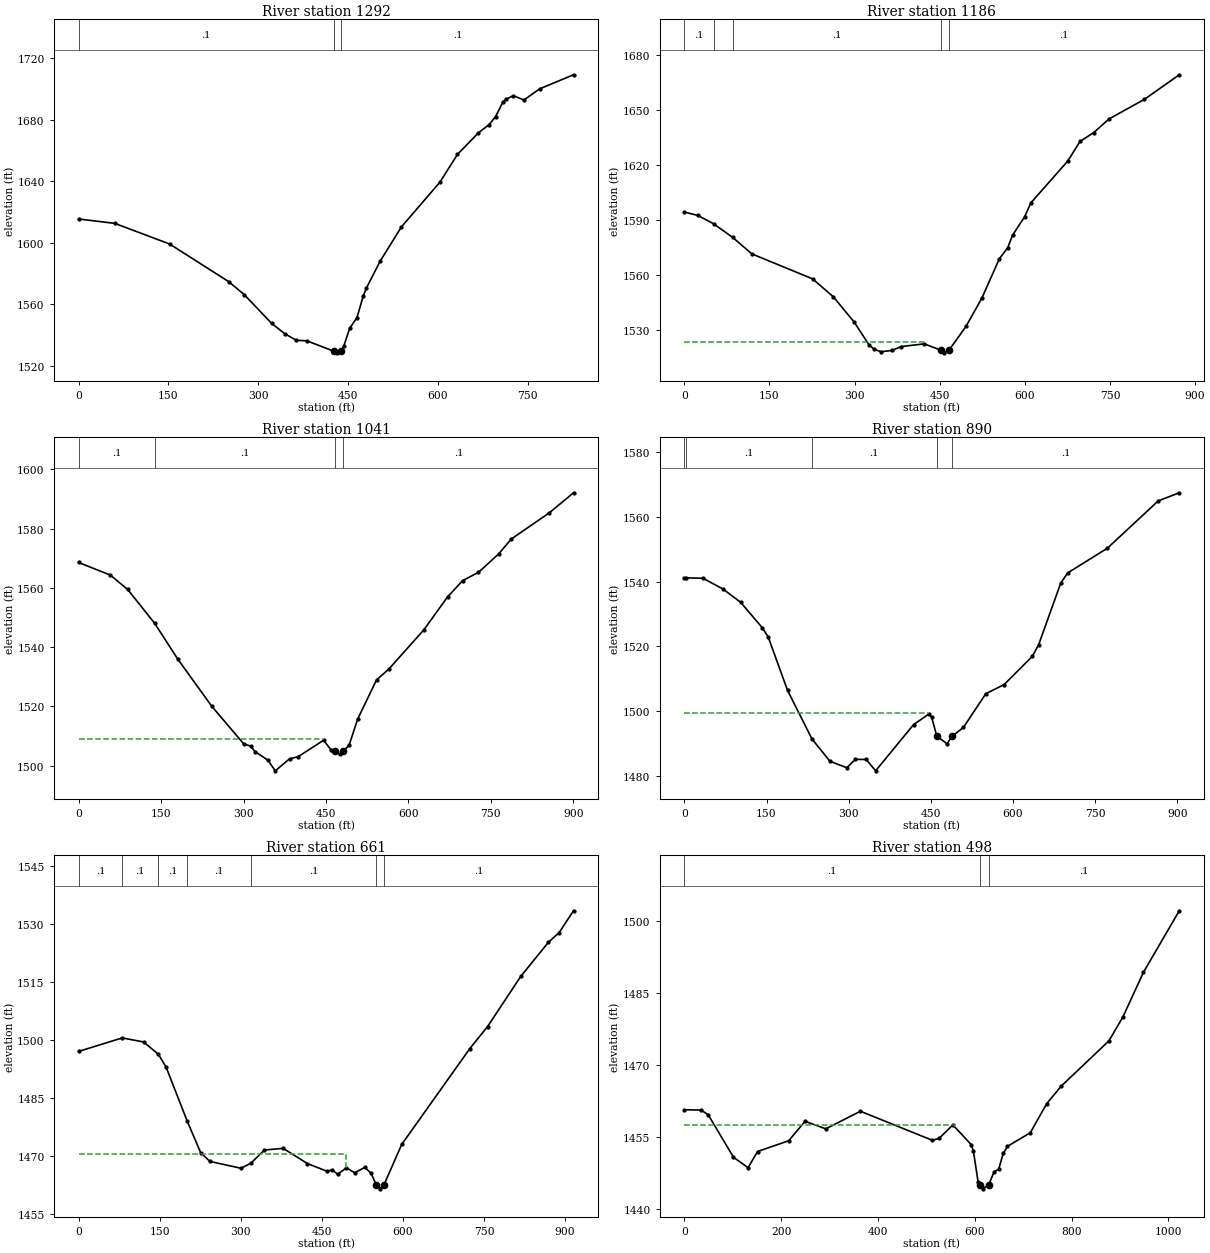
Type RM Length L Ch R = 1 ,1292    ,106.2,106,105.8
XS GIS Cut Line= 4
2487160.75924597627904.702373201   2486984.14542627644.142469445
2486811.89242923  627482.7915667 2486611.2940096627294.185443897
#Sta/Elev= 30
       0 1615.45    60.4 1612.61     152  1599.2   250.4 1574.83   276.4 1566.41
   322.3 1547.68   344.1 1541.03   363.4 1536.74     381 1536.41   425.61529.704
   431.8  1528.6  438.341529.705   442.8 1533.12   452.5 1544.51   464.7 1551.51
   475.1 1565.45   480.4 1570.62   503.4 1588.11   538.9 1610.34   603.2 1639.39
   632.4 1657.34   667.4 1671.39     685 1676.59   695.9  1681.8   708.3 1691.36
   714.2 1693.28   725.8 1695.49   743.4 1692.63   769.4 1699.88   826.1 1709.03
#Mann= 3 ,-1 , 0
       0      .1       0   425.6    .045       0  438.34      .1       0
Bank Sta=425.6,438.34
XS Rating Curve= 0 ,0
Exp/Cntr(USF)=0,0
Exp/Cntr=0.3,0.1

Type RM Length L Ch R = 1 ,1186    ,144.5,145.7,147.2
XS GIS Cut Line= 4
2487286.26186998 627843.231944382487045.48873257627559.089732524
2486840.60724296627369.1630961792486676.10385715627222.605534274
#Sta/Elev= 30
       0 1594.21      24 1592.32   51.471587.809   85.291580.322   119.1 1571.35
   225.9 1557.76   262.6 1547.95   299.3 1534.15   325.5 1521.69   334.8 1519.26
   346.5 1518.01     366 1518.68   381.6 1520.79   422.6 1522.28   452.5  1518.8
     458 1517.39   466.9 1519.13   496.2 1531.76   524.5 1547.39   555.1 1568.75
   569.8 1574.71   578.3 1581.55   599.8 1591.73   610.7 1599.25   675.7 1622.06
   697.2 1632.72   721.4 1637.55   748.2 1644.96   810.6 1655.67872.1266 1669.09
#Mann= 5 ,-1 , 0
       0      .1       0   51.47      .1       0   85.29      .1       0
   452.5    .045       0   466.9      .1       0
#XS Ineff= 2 , 0
           423.4 1523.52
Permanent Ineff=
       F       F
Bank Sta=452.5,466.9
XS Rating Curve= 0 ,0
Exp/Cntr(USF)=0,0
Exp/Cntr=0.3,0.1

Type RM Length L Ch R = 1 ,1041    ,153.5,150.6,146.7
XS GIS Cut Line= 4
 2487404.4052107627774.4396194042487175.59595589627508.243231455
2486988.66029019627279.4339766452486804.71559515627104.462193555
#Sta/Elev= 30
       0 1568.55    57.6 1564.31    89.1 1559.48  138.541547.975   180.5  1535.9
     242 1520.07   300.1 1507.36   312.9 1506.53   321.2 1504.68   344.1 1501.84
   357.9  1498.2   383.8 1502.27   399.3 1502.96   445.7 1508.53   459.8 1505.14
   466.3 1504.79   474.8  1503.8   481.9 1504.85   492.2  1506.9   507.7 1515.68
     542  1528.9   564.5 1532.58   628.3 1545.85   671.2 1556.93   698.8 1562.44
   727.4 1565.21   764.2 1571.44   787.1 1576.47   856.2 1585.29900.3538 1592.09
#Mann= 4 ,-1 , 0
       0      .1       0  138.54      .1       0   466.3    .045       0
   481.9      .1       0
#XS Ineff= 2 , 0
          445.45 1508.94
Permanent Ineff=
       F       F
Bank Sta=466.3,481.9
XS Rating Curve= 0 ,0
Exp/Cntr(USF)=0,0
Exp/Cntr=0.3,0.1

Type RM Length L Ch R = 1 ,890     ,228.6,229.1,222.2
XS GIS Cut Line= 4
2487531.52146337627665.2691906392487305.70317921627387.108920085
2487138.20882275627282.4249472972486895.94020001627032.678897929
#Sta/Elev= 30
       0 1541.09    3.73 1541.15      34 1541.02    70.5 1537.69   102.8  1533.6
   142.2 1525.75     153 1522.93   188.5 1506.37   232.9 1491.43   265.8 1484.52
   296.7 1482.51   312.1 1485.09   332.1 1485.08   349.2 1481.56   418.6 1495.84
   446.7 1499.11   451.4 1498.22   460.8 1492.35   479.7 1489.89   488.3 1492.17
   509.6 1494.97   550.5 1505.38   583.8 1508.18   635.5 1516.92   646.9 1520.49
   687.2 1539.48     700 1542.67   772.5  1550.3   865.3  1564.9903.7479 1567.41
#Mann= 5 ,-1 , 0
       0      .1       0    3.73      .1       0   232.9      .1       0
   460.8    .045       0   488.3      .1       0
#XS Ineff= 2 , 0
          445.45 1499.47
Permanent Ineff=
       F       F
Bank Sta=460.8,488.3
XS Rating Curve= 0 ,0
Exp/Cntr(USF)=0,0
Exp/Cntr=0.3,0.1

Type RM Length L Ch R = 1 ,661     ,163.9,162.5,161.2
XS GIS Cut Line= 4
2487676.58353995627508.2432314552487371.50453354627200.173254391
2487186.06435317627065.5795750912486972.20995161626930.985895791
#Sta/Elev= 30
       0 1497.02   80.71 1500.51   120.1 1499.47  147.461496.297   161.8 1492.97
   201.11478.908   225.7 1470.86   242.7 1468.56   300.3 1466.79  318.441468.064
   343.7 1471.51   378.4 1471.93   423.3    1468   459.2 1466.02   469.4  1466.4
     479  1465.2   495.2 1466.89   510.7 1465.62   529.5 1467.02     541 1465.48
  550.59 1462.46   558.1 1461.46  564.71 1462.46   597.6 1472.94   723.3 1497.69
   756.4 1503.45   817.9 1516.44   868.7 1525.22   888.8 1527.77915.3873 1533.41
#Mann= 7 ,-1 , 0
       0      .1       0   80.71      .1       0  147.46      .1       0
   201.1      .1       0  318.44      .1       0  550.59    .045       0
  564.71      .1       0
#XS Ineff= 2 , 0
          493.82 1470.39
Permanent Ineff=
       F       F
Bank Sta=550.59,564.71
XS Rating Curve= 0 ,0
Exp/Cntr(USF)=0,0
Exp/Cntr=0.3,0.1

Type RM Length L Ch R = 1 ,498     ,157.8,157.5,153
XS GIS Cut Line= 4
2487848.56435239627406.5502293182487467.21559437627065.579575091
2487301.21672324626960.8956023022487005.11062878626854.716144187
#Sta/Elev= 30
       0 1460.72    34.6 1460.66    49.2 1459.68   101.5 1450.84   131.5 1448.66
   151.2 1452.03   215.5 1454.27   249.3 1458.32   292.2 1456.75   363.7 1460.41
   512.1 1454.37   526.3 1454.77   554.7 1457.57   592.5 1453.47   597.2 1452.05
   606.7 1445.78  609.971445.077   616.1 1444.26  628.751445.077   639.8  1447.8
   649.3 1448.35   658.8 1451.68   667.5 1453.11   714.7 1455.94   748.3 1461.96
   778.4 1465.63   877.1 1475.07   905.9 1480.03   948.4 1489.341022.373 1502.14
#Mann= 3 ,-1 , 0
       0      .1       0  609.97    .045       0  628.75      .1       0
#XS Ineff= 2 , 0
          558.28  1457.5
Permanent Ineff=
       F       F
Bank Sta=609.97,628.75
XS Rating Curve= 0 ,0
Exp/Cntr(USF)=0,0
Exp/Cntr=0.5,0.3

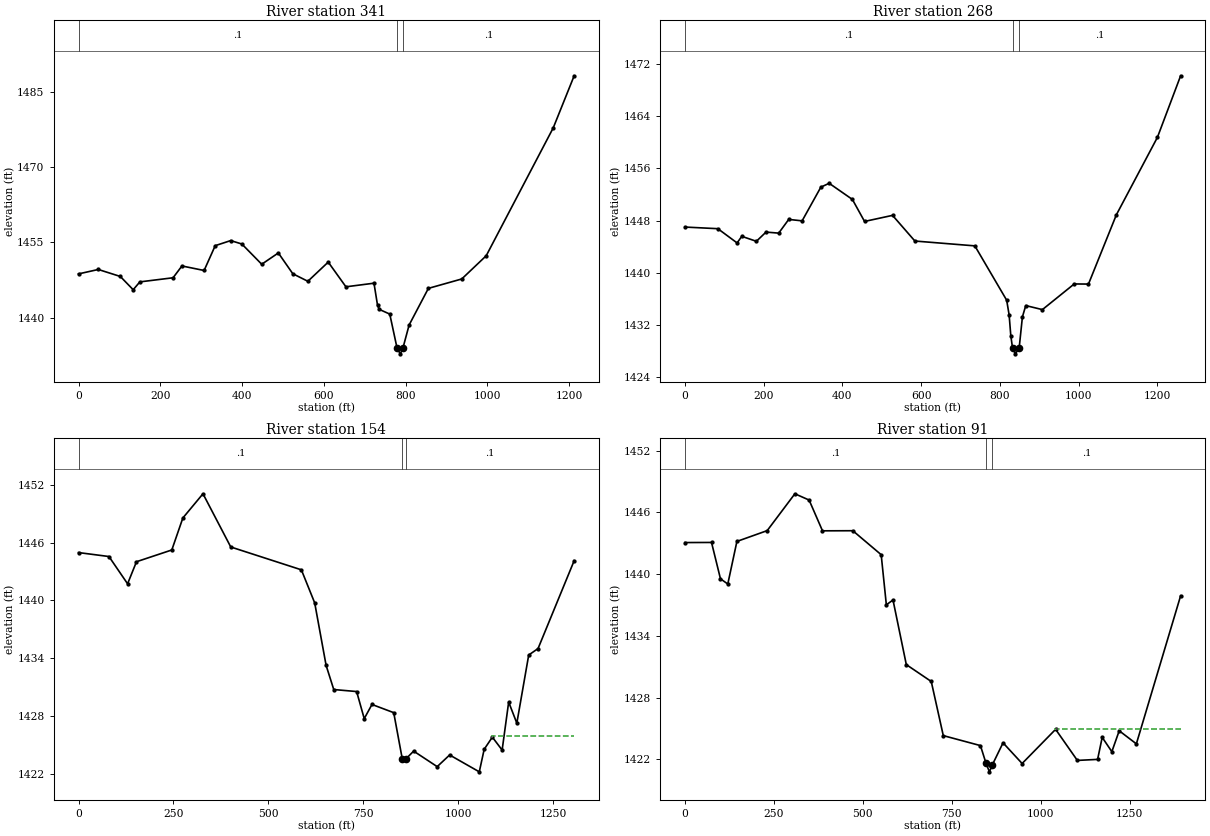
Type RM Length L Ch R = 1 ,341     ,75.3,72.8,72.2
XS GIS Cut Line= 4
2487908.38376541627397.5773173642487447.77428514626893.598762652
2487190.55080914 626793.401245842486945.29121575626730.590862166
#Sta/Elev= 30
       0 1448.75    48.4 1449.63   102.2 1448.24   133.7  1445.6     150 1447.16
   231.2 1447.98   252.9 1450.33   307.1 1449.43   334.3 1454.37   372.1 1455.38
   399.4  1454.7     448 1450.67   488.6 1452.92     524 1448.78   560.8 1447.28
   610.6  1451.1   653.9 1446.18   722.5  1446.9   731.1 1442.54   735.4 1441.69
   761.1 1440.75  779.061433.926   786.9 1432.84  793.061433.926   808.4 1438.58
   855.5 1445.87   937.1 1447.74   996.9 1452.36  1160.9 1477.83 1211.98 1488.18
#Mann= 3 ,-1 , 0
       0      .1       0  779.06    .045       0  793.06      .1       0
#XS Ineff= 2 , 0
       0     754  1437.9     818       0  1437.9
Permanent Ineff=
       F       F
Bank Sta=779.06,793.06
XS Rating Curve= 0 ,0
Exp/Cntr(USF)=0,0
Exp/Cntr=0.5,0.3

Type RM Length L Ch R = 1 ,268     ,113,114.4,116
XS GIS Cut Line= 4
2487929.32055997627384.1179494342487435.81040254626812.842555072
2487266.82056075626756.0141127012486954.26412771626663.294022516
#Sta/Elev= 30
       0 1447.02    83.5 1446.77   132.4 1444.59   144.3  1445.6   181.4 1444.84
   205.9 1446.25   238.1 1446.09   263.6 1448.19   297.6 1447.97   345.2 1453.13
   366.3 1453.72   425.3 1451.25   456.2 1447.88   527.3 1448.81   584.1 1444.88
   736.4 1444.14   817.3 1435.82   823.5 1433.58   827.8 1430.37  832.211428.492
   839.4 1427.61  848.991428.492   857.3 1433.28   865.8    1435     908 1434.38
   988.9 1438.31  1025.1 1438.29    1096  1448.9  1200.3 1460.761259.231 1470.18
#Mann= 3 ,-1 , 0
       0      .1       0  832.21    .045       0  848.99      .1       0
Bank Sta=832.21,848.99
XS Rating Curve= 0 ,0
Exp/Cntr(USF)=0,0
Exp/Cntr=0.5,0.3

Type RM Length L Ch R = 1 ,154     ,62.8,62.5,64.3
XS GIS Cut Line= 4
2487924.83410399627334.7669336912487465.72010905626729.095376841
  2487281.775414626609.4565507962486978.19189292626489.817724752
#Sta/Elev= 30
       0 1444.97    80.2 1444.56   129.3 1441.73   152.7 1444.02   245.8 1445.24
   274.9 1448.56   327.9 1451.07   401.1 1445.55   587.1 1443.18   622.2 1439.75
   652.3 1433.26   672.4 1430.76   732.7 1430.55   752.7 1427.74   773.1 1429.21
   830.4 1428.36  852.73  1423.6  863.13 1423.59   882.9 1424.37   944.9 1422.76
   977.7 1423.97  1055.8 1422.22  1068.7 1424.56  1090.2 1425.82    1116 1424.48
  1133.2 1429.46  1154.7 1427.27    1186 1434.34  1210.6 1435.011305.752 1444.13
#Mann= 3 ,-1 , 0
       0      .1       0  852.73    .045       0  863.13      .1       0
#XS Ineff= 2 , 0
                         1088.98         1425.98
Permanent Ineff=
       F       F
Bank Sta=852.73,863.13
XS Rating Curve= 0 ,0
Exp/Cntr(USF)=0,0
Exp/Cntr=0.3,0.1

Type RM Length L Ch R = 1 ,91      ,,,
XS GIS Cut Line= 4
 2487942.7799279627315.3256244592487441.79234384626651.330139912
2487350.56773898626563.0965057042486952.76864238 626389.62020794
#Sta/Elev= 30
       0 1443.07    74.6 1443.08    99.7 1439.55   120.3 1439.04   145.9 1443.18
     231 1444.23   308.8 1447.81   348.8  1447.2   386.4 1444.21   471.6 1444.22
   551.3 1441.89   565.8 1437.02   584.5 1437.49   621.9 1431.21     692 1429.57
   725.8 1424.31   830.2 1423.34  845.641421.647   855.4 1420.79   863.9 1421.49
   893.7 1423.61   947.3  1421.6  1041.4 1424.92  1102.5  1421.9  1159.4    1422
  1172.3 1424.14  1199.4 1422.75  1220.1 1424.78  1268.3 1423.511392.686  1437.9
#Mann= 3 ,-1 , 0
       0      .1       0  845.64    .045       0   863.9      .1       0
#XS Ineff= 2 , 0
                         1038.33         1424.97
Permanent Ineff=
       F       F
Bank Sta=845.64,863.9
XS Rating Curve= 0 ,0
Exp/Cntr(USF)=0,0
Exp/Cntr=0.3,0.1
LCMann Table=0

Chan Stop Cuts=-1
Use User Specified Reach Order=0
Composite Channel Slope=5